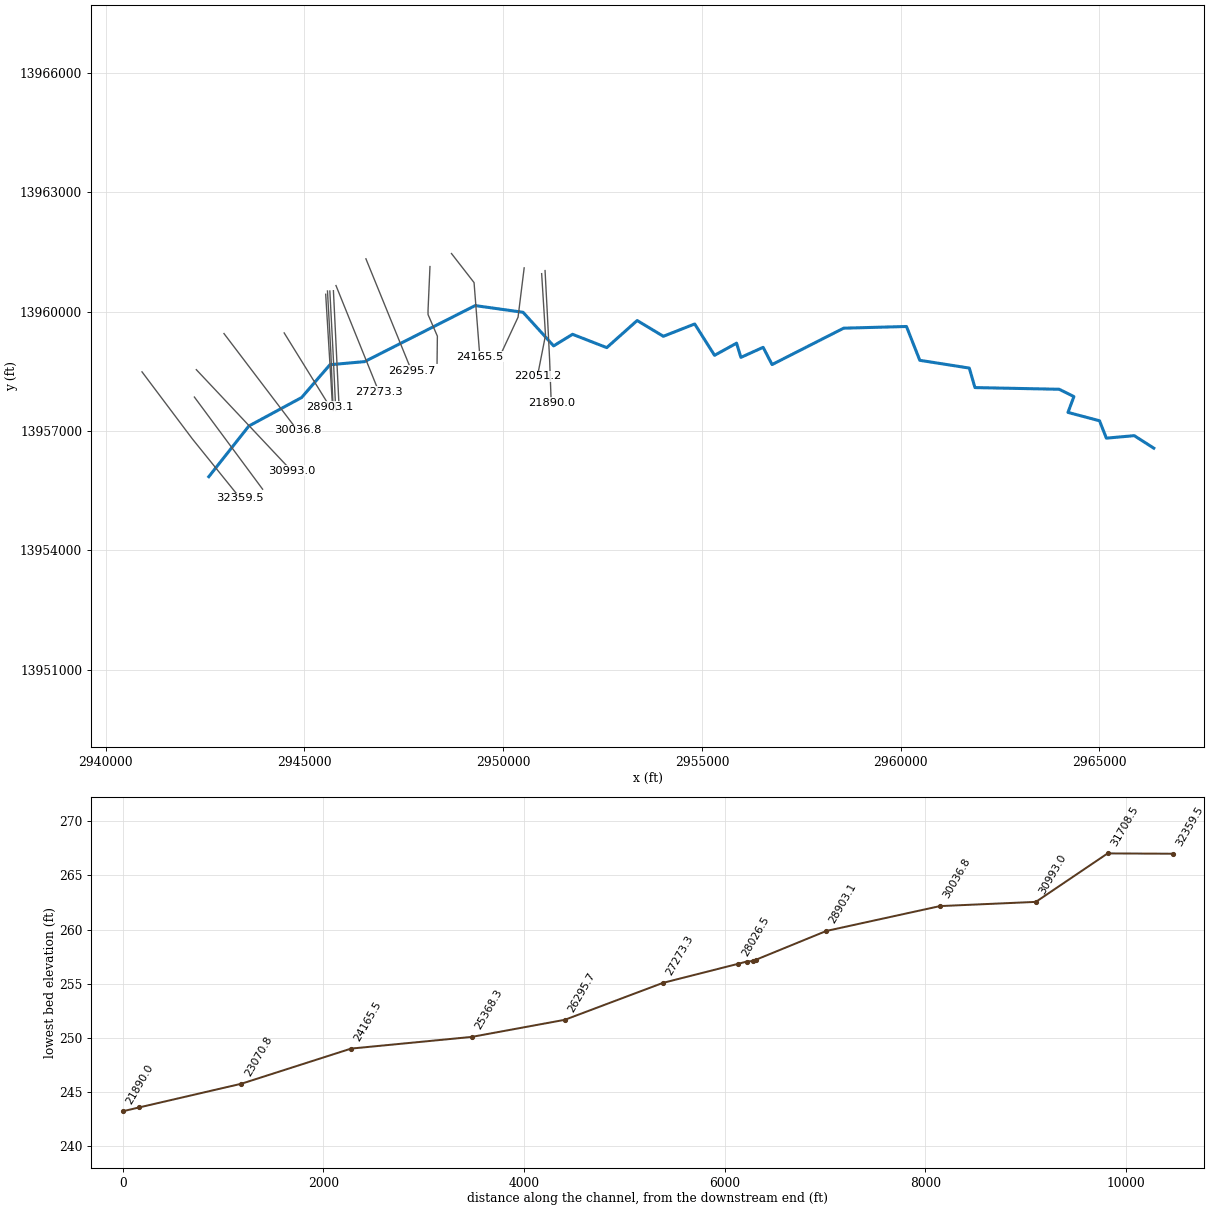
--- J158-00-00.PRJ (project) ---

Proj Title=J158-00-00
Current Plan=p03
Default Exp/Contr=.3,.1
English Units
Geom File=g01
Flow File=f02
Flow File=f03
Plan File=p02
Plan File=p03
Y Axis Title=Elevation
X Axis Title(PF)=Main Channel Distance
X Axis Title(XS)=Station
BEGIN DESCRIPTION:
Spring Creek
HCFCD Unit J158-00-00
Flood Hazard Model
10, 2, 1, 0.2% Event
Filename J158-00-00.prj
Prepared by: Halff Associates, Inc. Date: 03/24/2004
Reviewed by:                  Date:
STATUS Final RAS
END DESCRIPTION:
DSS File=dss
DSS Export Rating Curves= 0
DSS Export Rating Curve Sorted= 0
DSS Export Volume Flow Curves= 0
DXF OffsetX= 0
DXF OffsetY= 0
DXF ScaleX= 1
DXF ScaleY= 10

--- J158-00-00.p03 (plan) ---

Plan Title=Floodway
Version=Version 3.0.1  Mar 2001
Short Identifier=Floodway0607
Geom File=g01
Flow File=f03
Subcritical Flow
K Sum by GR= 0
Std Step Tol= 0.01
Critical Tol= 0.01
Num of Std Step Trials= 20
Max Error Tol= 0.3
Flow Tol Ratio= 0.001
Split Flow NTrial= 30
Split Flow Tol= 0.02
Split Flow Ratio= 0.02
Log Output Level= 0
Friction Slope Method= 1
Unsteady Friction Slope Method= 2
Parabolic Critical Depth
Global Vel Dist= 0 , 0 , 0
Global Log Level= 0
CheckData=True
Encroach Param=-1 ,0,0, 7
Encroach River=J158-00-00
Encroach Reach=Reach - 1
Encroach Node=32359.5
       1    4765    5031       0       0       0       0       0       0
       0       0       0       0       0       0       0       0       0
Encroach Node=31708.5
       1    4740    5040       0       0       0       0       0       0
       0       0       0       0       0       0       0       0       0
Encroach Node=30993.0
       1    4800    5115       4      .7               4      .8
       4      .9               4       1               4     1.1
Encroach Node=30036.8
       1    4680    5065       4      .7               4      .8
       4      .9               4       1               4     1.1
Encroach Node=28903.1
       1    4790    5030       4      .7               4      .8
       4      .9               4       1               4     1.1
Encroach Node=28204.2
       1    4800    5290       4      .7               4      .8
       4      .9               4       1               4     1.1
Encroach Node=28171.8
       1    4800    5285       4      .7               4      .8
       4      .9               4       1               4     1.1
Encroach Node=28140.3
       1    4800    5275       4      .7               4      .8
       4      .9               4       1               4     1.1
Encroach Node=28108.8
       1    4800    5275       4      .7               4      .8
       4      .9               4       1               4     1.1
Encroach Node=28026.5
       1    4805    5275       4      .7               4      .8
       4      .9               4       1               4     1.1
Encroach Node=27273.3
       1    4640    5080       4      .7               4      .8
       4      .9               4       1               4     1.1
Encroach Node=26295.7
       1    4750    5075       4      .7               4      .8
       4      .9               4       1               4     1.1
Encroach Node=25368.3
       1    4770    5052       4      .7               4      .8
       4      .9               4       1               4     1.1
Encroach Node=24165.5
       1    4750    5100       4      .7               4      .8
       4      .9               4       1               4     1.1
Encroach Node=23070.8
       1    4750    5126       4      .7               4      .8
       4      .9               4       1               4     1.1
Encroach Node=22051.2
       1    4570    5160       4      .7               4      .8
       4      .9               4       1               4     1.1
Encroach Node=21890.0
       1    4530    5100       4      .7               4      .8
       4      .9               4       1               4     1.1
Encroach Node=21861.0
       1    4570    5100       4      .7               4      .8
       4      .9               4       1               4     1.1
Encroach Node=21832.0
       1    4580    5100       4      .7               4      .8
       4      .9               4       1               4     1.1
Encroach Node=21721.5
       1    4590    5100       4      .7               4      .8
       4      .9               4       1               4     1.1
Encroach Node=20657.4
       1    4830    5065       4      .7               4      .8
       4      .9               4       1               4     1.1
Encroach Node=19547.3
       1    4680    5050       4      .7               4      .8
       4      .9               4       1               4     1.1
Encroach Node=18132.0
       1    4670    5051       4      .7               4      .8
       4      .9               4       1               4     1.1
Encroach Node=17274.9
       1    4890    5440       4      .7               4      .8
       4      .9               4       1               4     1.1
Encroach Node=16409.9
       1    4830    5210       4      .7               4      .8
       4      .9               4       1               4     1.1
Encroach Node=15926.3
       1    4720    5265       4      .7               4      .8
       4      .9               4       1               4     1.1
Encroach Node=15728.9
       1    4780    5385       4      .7               4      .8
       4      .9               4       1               4     1.1
Encroach Node=15696.4
       1    4800    5385       4      .7               4      .8
       4      .9               4       1               4     1.1
Encroach Node=15663.9
       1    4800    5430       4      .7               4      .8
       4      .9               4       1               4     1.1
Encroach Node=15526.3
       1    4835    5480       4      .7               4      .8
       4      .9               4       1               4     1.1
Encroach Node=14338.1
       1    4915    5575       4      .7               4      .8
       4      .9               4       1               4     1.1
Encroach Node=13495.5
       1    4910    5370       4      .7               4      .8
       4      .9               4       1               4     1.1
Encroach Node=12890.2
       1    4790    5325       4      .7               4      .8
       4      .9               4       1               4     1.1
Encroach Node=11519.0
       1    4940    5225       4      .7               4      .8
       4      .9               4       1               4     1.1
Encroach Node=10125.8
       1    4865    5230       4      .7               4      .8
       4      .9               4       1               4     1.1
Encroach Node=8594.7
       1    4740    5030       4      .7               4      .8
       4      .9               4       1               4     1.1
Encroach Node=7480.8
       1    4825    5212       0       0       0       0       0       0
       0       0       0       0       0       0       0       0       0
Encroach Node=6709.4
       1    4495    5045       4      .7               4      .8
       4      .9               4       1               4     1.1
Encroach Node=5204.0
       1    4800    5120       4      .7               4      .8
       4      .9               4       1               4     1.1
Encroach Node=4514.6
       1    4690    5120       4      .7               4      .8
       4      .9               4       1               4     1.1
Encroach Node=2825.5
       1    4775    5100       4      .7               4      .8
       4      .9               4       1               4     1.1
Encroach Node=1045.8
       1    4605    5120       4      .7               4      .8
       4      .9               4       1               4     1.1
Encroach Reach=J158-00-00_0010
Encroach Node=32359.5
       1    4765    5031       0       0       0       0       0       0
       0       0       0       0       0       0       0       0       0
Encroach Node=31708.5
       1    4740    5040       0       0       0       0       0       0
       0       0       0       0       0       0       0       0       0
Encroach Node=30993.0
       1    4800    5115       0       0       0       0       0       0
       0       0       0       0       0       0       0       0       0
Encroach Node=30036.8
       1    4680    5065       0       0       0       0       0       0
       0       0       0       0       0       0       0       0       0
Encroach Node=28903.1
       1    4790    5030       0       0       0       0       0       0
       0       0       0       0       0       0       0       0       0
Encroach Node=28204.2
       1    4800    5290       0       0       0       0       0       0
       0       0       0       0       0       0       0       0       0
Encroach Node=28171.8
       1    4800    5285       0       0       0       0       0       0
       0       0       0       0       0       0       0       0       0
Encroach Node=28140.3
       1    4800    5275       0       0       0       0       0       0
       0       0       0       0       0       0       0       0       0
Encroach Node=28108.8
       1    4800    5275       0       0       0       0       0       0
       0       0       0       0       0       0       0       0       0
Encroach Node=28026.5
       1    4805    5275       0       0       0       0       0       0
       0       0       0       0       0       0       0       0       0
Encroach Node=27273.3
       1    4640    5080       0       0       0       0       0       0
       0       0       0       0       0       0       0       0       0
Encroach Node=26295.7
       1    4750    5075       0       0       0       0       0       0
       0       0       0       0       0       0       0       0       0
Encroach Node=25368.3
       1    4770    5052       0       0       0       0       0       0
       0       0       0       0       0       0       0       0       0
Encroach Node=24165.5
       1    4750    5100       0       0       0       0       0       0
       0       0       0       0       0       0       0       0       0
Encroach Node=23070.8
       1    4750    5126       0       0       0       0       0       0
       0       0       0       0       0       0       0       0       0
Encroach Node=22051.2
       1    4570    5160       0       0       0       0       0       0
       0       0       0       0       0       0       0       0       0
Encroach Node=21890.0
       1    4530    5100       0       0       0       0       0       0
       0       0       0       0       0       0       0       0       0
Encroach Node=21861.0
       1    4570    5100       0       0       0       0       0       0
       0       0       0       0       0       0       0       0       0
Encroach Node=21832.0
       1    4580    5100       0       0       0       0       0       0
       0       0       0       0       0       0       0       0       0
Encroach Node=21721.5
       1    4590    5100       0       0       0       0       0       0
       0       0       0       0       0       0       0       0       0
Encroach Node=20657.4
       1    4830    5065       0       0       0       0       0       0
       0       0       0       0       0       0       0       0       0
Encroach Node=19547.3
       1    4680    5050       0       0       0       0       0       0
       0       0       0       0       0       0       0       0       0
Encroach Node=18132.0
       1    4670    5051       0       0       0       0       0       0
       0       0       0       0       0       0       0       0       0
Encroach Node=17274.9
       1    4890    5440       0       0       0       0       0       0
       0       0       0       0       0       0       0       0       0
Encroach Node=16409.9
       1    4830    5210       0       0       0       0       0       0
       0       0       0       0       0       0       0       0       0
Encroach Node=15926.3
       1    4720    5265       0       0       0       0       0       0
       0       0       0       0       0       0       0       0       0
Encroach Node=15728.9
       1    4780    5385       0       0       0       0       0       0
       0       0       0       0       0       0       0       0       0
Encroach Node=15696.4
       1    4800    5385       0       0       0       0       0       0
       0       0       0       0       0       0       0       0       0
Encroach Node=15663.9
       1    4800    5430       0       0       0       0       0       0
       0       0       0       0       0       0       0       0       0
Encroach Node=15526.3
       1    4835    5480       0       0       0       0       0       0
       0       0       0       0       0       0       0       0       0
Encroach Node=14338.1
       1    4915    5575       0       0       0       0       0       0
       0       0       0       0       0       0       0       0       0
Encroach Node=13495.5
       1    4910    5370       0       0       0       0       0       0
       0       0       0       0       0       0       0       0       0
Encroach Node=12890.2
       1    4790    5325       0       0       0       0       0       0
       0       0       0       0       0       0       0       0       0
Encroach Node=11519.0
       1    4940    5225       0       0       0       0       0       0
       0       0       0       0       0       0       0       0       0
Encroach Node=10125.8
       1    4865    5230       0       0       0       0       0       0
       0       0       0       0       0       0       0       0       0
Encroach Node=8594.7
       1    4740    5030       0       0       0       0       0       0
       0       0       0       0       0       0       0       0       0
Encroach Node=7480.8
       1    4825    5212       0       0       0       0       0       0
       0       0       0       0       0       0       0       0       0
Encroach Node=6709.4
       1    4495    5045       0       0       0       0       0       0
       0       0       0       0       0       0       0       0       0
Encroach Node=5204.0
       1    4800    5120       0       0       0       0       0       0
       0       0       0       0       0       0       0       0       0
Encroach Node=4514.6
       1    4690    5120       0       0       0       0       0       0
       0       0       0       0       0       0       0       0       0
Encroach Node=2825.5
       1    4775    5100       0       0       0       0       0       0
       0       0       0       0       0       0       0       0       0
Encroach Node=1045.8
       1    4605    5120       0       0       0       0       0       0
       0       0       0       0       0       0       0       0       0
Computation Interval=1HOUR
Output Interval=1HOUR
Run HTab= 0
Run UNet= 0
Run PostProcess= 0
UNET Theta= 1
UNET ZTol= 0.02
UNET ZSATol= 0.1
UNET MxIter= 20
UNET MaxInSteps= 20
UNET DtIC= 0
UNET DtMin= 0
UNET MaxCRTS= 20
UNET WFStab= 2
UNET SFStab= 1
UNET WFX= 1
UNET SFX= 1
UNET Convert EG Bridges=-1
UNET Use Existing IB Tables=-1
Instantaneous Interval=1HOUR
DSS File=dss
Write IC File= 0
Write Velocity= 0
Write Detailed= 0

--- J158-00-00.p02 (plan) ---

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Plan Title=FEMA Effective June 200
Short Identifier=FEMAeff0607
Geom File=g01
Flow File=f02
Encroach Param=-1 ,0,0, 0

--- J158-00-00.f03 (steady flow) ---

Flow Title=Floodway
Version=Version 3.0.1  Mar 2001
Number of Profiles= 2
Profile Names=1PCT_100yr, 1PCTFloodway_100yrFW
River Rch & RM=J158-00-00,J158-00-00_0010,32359.5
     810     810
River Rch & RM=J158-00-00,J158-00-00_0010,28026.5
    2020    2020
River Rch & RM=J158-00-00,J158-00-00_0010,27273.3
    2180    2180
River Rch & RM=J158-00-00,J158-00-00_0010,26295.7
    2340    2340
River Rch & RM=J158-00-00,J158-00-00_0010,25368.3
    2580    2580
River Rch & RM=J158-00-00,J158-00-00_0010,24165.5
    2810    2810
River Rch & RM=J158-00-00,J158-00-00_0010,23070.8
    3050    3050
River Rch & RM=J158-00-00,J158-00-00_0010,22051.2
    3100    3100
River Rch & RM=J158-00-00,J158-00-00_0010,21832.0
    3310    3310
River Rch & RM=J158-00-00,J158-00-00_0010,20657.4
    3520    3520
River Rch & RM=J158-00-00,J158-00-00_0010,19547.3
    3810    3810
River Rch & RM=J158-00-00,J158-00-00_0010,18132.0
    3990    3990
River Rch & RM=J158-00-00,J158-00-00_0010,17274.9
    4190    4190
River Rch & RM=J158-00-00,J158-00-00_0010,16409.9
    4300    4300
River Rch & RM=J158-00-00,J158-00-00_0010,15926.3
    4400    4400
River Rch & RM=J158-00-00,J158-00-00_0010,15526.3
    4530    4530
River Rch & RM=J158-00-00,J158-00-00_0010,13495.5
    4660    4660
River Rch & RM=J158-00-00,J158-00-00_0010,11519
    4870    4870
River Rch & RM=J158-00-00,J158-00-00_0010,8594.7
    5000    5000
River Rch & RM=J158-00-00,J158-00-00_0010,6709.4
    5100    5100
River Rch & RM=J158-00-00,J158-00-00_0010,4514.6
    5180    5180
River Rch & RM=J158-00-00,J158-00-00_0010,2825.5
    5314    5314
Boundary for River Rch & Prof#=J158-00-00,J158-00-00_0010, 1
Up Type= 0
Dn Type= 3
Dn Slope=.0013
Boundary for River Rch & Prof#=J158-00-00,J158-00-00_0010, 2
Up Type= 0
Dn Type= 1
Dn Known WS=222.68
DSS Import GetInterval= 0
DSS Import GetPeak= 0
DSS Import FillOption= 0

--- J158-00-00.f02 (steady flow) ---

Flow Title=FEMA Effective June 2007
Version=Version 3.0.1  Mar 2001
Number of Profiles= 4
Profile Names=10PCT_10yr, 2PCT_50yr, 1PCT_100yr, 0.2PCT_500yr
River Rch & RM=J158-00-00,J158-00-00_0010,32359.5
     390     650     810    1300
River Rch & RM=J158-00-00,J158-00-00_0010,28026.5
     970    1690    2020    3080
River Rch & RM=J158-00-00,J158-00-00_0010,27273.3
    1050    1810    2180    3340
River Rch & RM=J158-00-00,J158-00-00_0010,26295.7
    1130    1940    2340    3600
River Rch & RM=J158-00-00,J158-00-00_0010,25368.3
    1240    2110    2580    3970
River Rch & RM=J158-00-00,J158-00-00_0010,24165.5
    1360    2290    2810    4340
River Rch & RM=J158-00-00,J158-00-00_0010,23070.8
    1470    2460    3050    4720
River Rch & RM=J158-00-00,J158-00-00_0010,22051.2
    1500    2500    3100    4800
River Rch & RM=J158-00-00,J158-00-00_0010,21832.0
    1600    2660    3310    5080
River Rch & RM=J158-00-00,J158-00-00_0010,20657.4
    1690    2820    3520    5360
River Rch & RM=J158-00-00,J158-00-00_0010,19547.3
    1830    3050    3810    5730
River Rch & RM=J158-00-00,J158-00-00_0010,18132.0
    1910    3190    3990    5980
River Rch & RM=J158-00-00,J158-00-00_0010,17274.9
    2000    3340    4190    6230
River Rch & RM=J158-00-00,J158-00-00_0010,16409.9
    2060    3430    4300    4380
River Rch & RM=J158-00-00,J158-00-00_0010,15926.3
    2100    3500    4400    6500
River Rch & RM=J158-00-00,J158-00-00_0010,15526.3
    2170    3610    4530    6720
River Rch & RM=J158-00-00,J158-00-00_0010,13495.5
    2230    3720    4660    6940
River Rch & RM=J158-00-00,J158-00-00_0010,11519
    2330    3890    4870    7270
River Rch & RM=J158-00-00,J158-00-00_0010,8594.7
    2400    4000    5000    7500
River Rch & RM=J158-00-00,J158-00-00_0010,6709.4
    2450    4110    5100    7700
River Rch & RM=J158-00-00,J158-00-00_0010,4514.6
    2490    4200    5180    7860
River Rch & RM=J158-00-00,J158-00-00_0010,2825.5
    2565    4358    5314    8132
Boundary for River Rch & Prof#=J158-00-00,J158-00-00_0010, 1
Up Type= 0
Dn Type= 3
Dn Slope=.0013
Boundary for River Rch & Prof#=J158-00-00,J158-00-00_0010, 2
Up Type= 0
Dn Type= 3
Dn Slope=.0013
Boundary for River Rch & Prof#=J158-00-00,J158-00-00_0010, 3
Up Type= 0
Dn Type= 3
Dn Slope=.0013
Boundary for River Rch & Prof#=J158-00-00,J158-00-00_0010, 4
Up Type= 0
Dn Type= 3
Dn Slope=.0013
DSS Import GetInterval= 0
DSS Import GetPeak= 0
DSS Import FillOption= 0

--- J158-00-00.g01 (geometry) ---

Geom Title=J158-00-00 June 2007
Version=Version 3.0.1  Mar 2001

River Reach=J158-00-00      ,J158-00-00_0010
Reach XY= 30
    2942595.0214   13955852.1461    2943602.8765   13957125.3493
    2944929.5945   13957840.9072    2945642.8135   13958665.7499
    2946513.9447   13958743.5212    2949296.3298   13960151.4152
    2950500.9245   13959983.1039    2951269.4217   13959138.6669
    2951744.9867       13959430.    2952606.8266   13959095.0829
    2953371.5836   13959776.5073    2954030.4984   13959380.1512
    2954818.6328   13959689.7013    2955317.7647    13958901.507
    2955871.5839   13959207.0619    2955980.9588   13958850.2911
    2956540.5446   13959102.6974    2956764.8124   13958669.7364
    2958565.1606   13959583.7992    2960145.6017   13959626.4821
    2960481.0518   13958776.6763    2961726.6894   13958581.3703
    2961868.6409   13958091.4293    2963987.0358   13958049.0761
    2964358.1549   13957865.4422    2964208.9688   13957467.4871
    2965002.6605   13957257.4089    2965174.6356   13956820.6642
    2965876.5897    13956883.225    2966368.2264    13956568.898

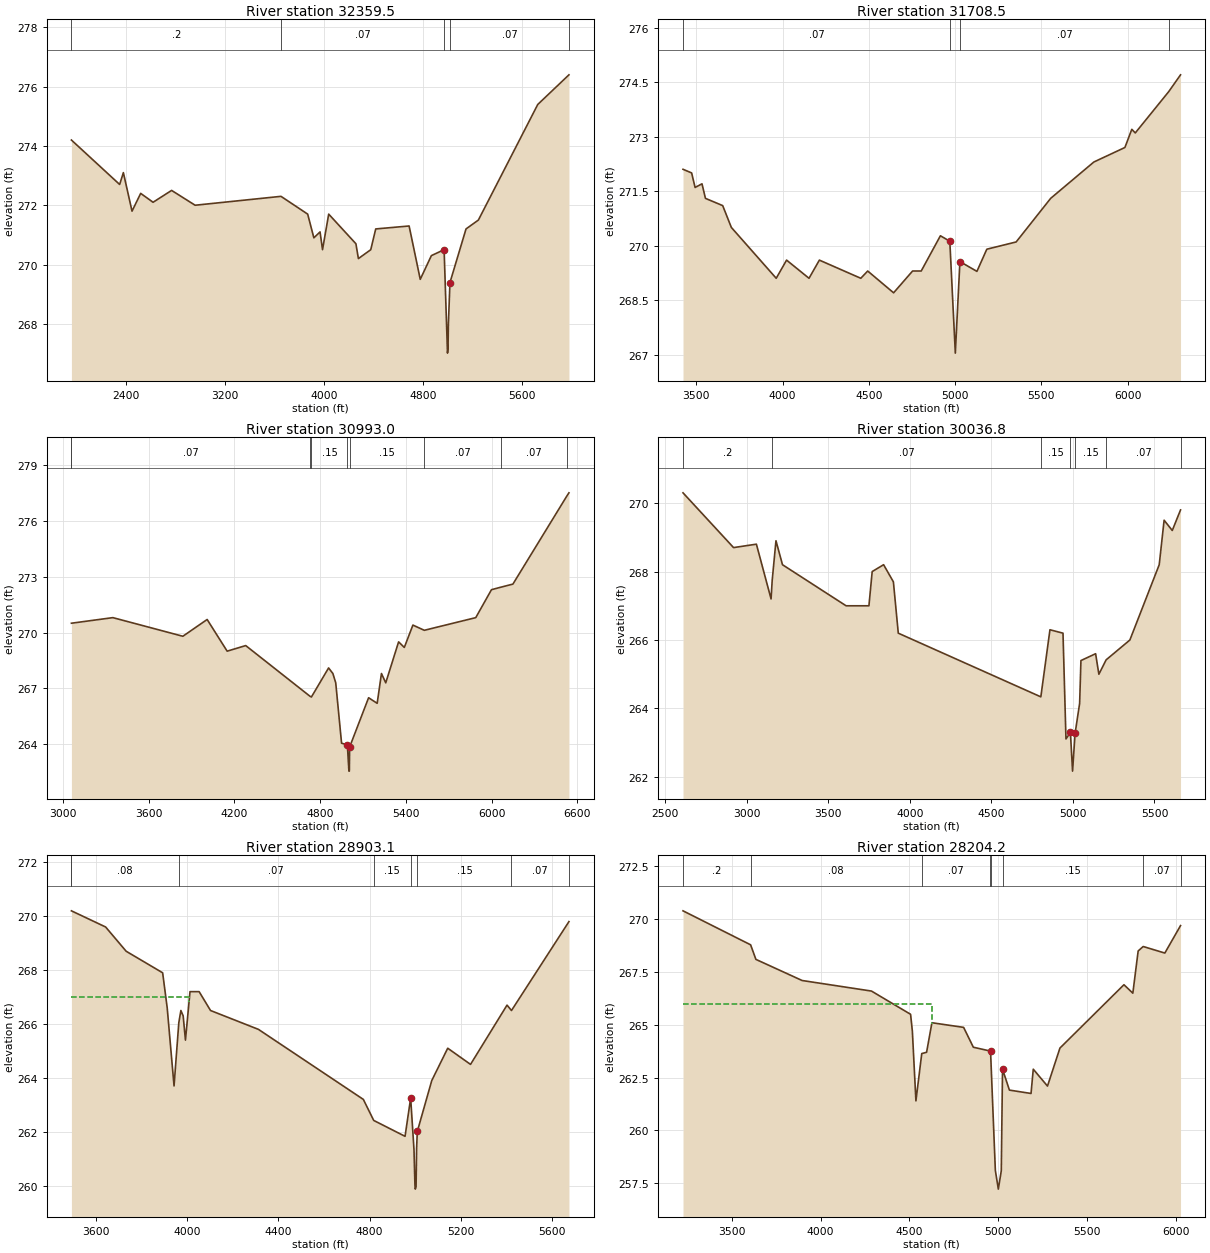
Type RM Length L Ch R = 1 ,32359.5 ,671.51,651,629.27
BEGIN DESCRIPTION:
Cross Section XS32
END DESCRIPTION:
XS GIS Cut Line= 3
    2940915.2091   13958486.4887    2942183.3813   13956800.0713
    2943384.8206   13955312.5749
#Sta/Elev= 30
  1959.9   274.2  2349.9   272.7  2379.9   273.1  2449.9   271.8  2519.9   272.4
  2619.9   272.1  2769.9   272.5  2959.9     272  3654.2   272.3  3869.9   271.7
  3919.9   270.9  3969.9   271.1  3989.9   270.5  4039.9   271.7  4259.9   270.7
  4279.9   270.2  4379.9   270.5  4419.9   271.2  4689.9   271.3  4779.9   269.5
  4869.9   270.3  4972.8   270.5  5000.2  267.01  5004.5  267.17  5007.4  267.99
  5020.1  269.39  5149.9   271.2  5249.9   271.5  5729.9   275.4    5982   276.4
#Mann= 5 , 1 , 0
  1959.9      .2       0  3654.2     .07       0  4972.8     .06       0
  5020.1     .07       0    5982      .2       0
Bank Sta=4972.8,5020.1
XS Rating Curve= 0
Exp/Cntr=.3,.1

Type RM Length L Ch R = 1 ,31708.5 ,622.56,715.5,724.81
BEGIN DESCRIPTION:
Cross Section XS31
END DESCRIPTION:
XS GIS Cut Line= 2
    2942232.8029   13957853.3774    2943949.1881   13955537.8766
#Sta/Elev= 30
  3423.6   272.1  3473.6     272  3493.6   271.6  3533.6   271.7  3553.6   271.3
  3653.6   271.1  3703.6   270.5  3963.6   269.1  4023.6   269.6  4153.6   269.1
  4213.6   269.6  4453.6   269.1  4493.6   269.3  4643.6   268.7  4753.6   269.3
  4803.6   269.3  4914.7  270.27  4969.3  270.12  5001.2  267.04  5027.8  269.56
  5126.3  269.29  5183.6   269.9  5353.6   270.1  5553.6   271.3  5803.6   272.3
  5983.6   272.7  6023.6   273.2  6043.6   273.1  6237.9  274.24  6305.9   274.7
#Mann= 4 ,-1 , 0
  3423.6     .07       0  4969.3     .06       0  5027.8     .07       0
  6237.9      .2       0
Bank Sta=4969.3,5027.8
XS Rating Curve= 0
Exp/Cntr=.3,.1

Type RM Length L Ch R = 1 ,30993.0 ,944.34,956.2,901.81
BEGIN DESCRIPTION:
Cross Section XS30
END DESCRIPTION:
XS GIS Cut Line= 2
    2942281.3798   13958541.5507     2944669.746   13956007.4537
#Sta/Elev= 30
  3059.5   270.5  3349.5   270.8  3839.5   269.8  4009.5   270.7  4149.5     269
  4279.5   269.3  4729.1  266.58  4739.3  266.54  4859.5   268.1  4889.5   267.8
  4909.5   267.3  4950.3  264.06  4990.9  263.97  5001.7  262.56  5004.7  262.56
  5006.6  263.85  5139.5   266.5  5199.5   266.2  5229.5   267.8  5259.5   267.3
  5349.5   269.5  5389.5   269.2  5449.5   270.4  5529.4  270.12  5889.5   270.8
  5999.5   272.3  6068.1  272.44  6149.5   272.6  6527.2  277.33  6541.7   277.5
#Mann= 9 , 1 , 0
  3059.5      .2       0  3059.5     .07       0  4729.1     .15       0
  4739.3     .15       0  4990.9     .06       0  5006.6     .15       0
  5529.4     .07       0  6068.1     .07       0  6527.2      .2       0
Bank Sta=4990.9,5006.6
XS Rating Curve= 0
Exp/Cntr=.3,.1

Type RM Length L Ch R = 1 ,30036.8 ,1137.94,1133.7,1058.7
BEGIN DESCRIPTION:
Cross Section XS29
END DESCRIPTION:
XS GIS Cut Line= 2
    2942977.6493   13959448.3203     2944823.573   13957019.4733
#Sta/Elev= 30
  2609.3   270.3  2919.3   268.7  3059.3   268.8  3149.3   267.2  3156.1  267.74
  3179.3   268.9  3219.3   268.2  3609.3     267  3749.3     267  3769.3     268
  3839.3   268.2  3899.3   267.7  3929.3   266.2  4803.4  264.34  4859.3   266.3
  4939.3   266.2  4957.5  263.11  4984.8   263.3  4997.9  262.17  5013.4  263.27
  5041.3  264.15  5049.3   265.4  5139.3   265.6  5159.3     265  5203.6  265.42
  5349.3     266  5529.3   268.2  5559.3   269.5  5609.3   269.2    5660   269.8
#Mann= 7 ,-1 , 0
  2609.3      .2       0  3156.1     .07       0  4803.4     .15       0
  4984.8     .06       0  5013.4     .15       0  5203.6     .07       0
    5660      .2       0
Bank Sta=4984.8,5013.4
XS Rating Curve= 0
Exp/Cntr=.3,.1

Type RM Length L Ch R = 1 ,28903.1 ,686.95,698.9,481.53
BEGIN DESCRIPTION:
Cross Section XS28
END DESCRIPTION:
XS GIS Cut Line= 2
    2944491.6306   13959464.5126    2945641.2849   13957610.4927
#Sta/Elev= 30
  3492.2   270.2  3642.2   269.6  3732.2   268.7  3892.2   267.9  3912.2   266.6
  3942.2   263.7  3963.1  266.05  3972.2   266.5  3982.2   266.3  3992.2   265.4
  4012.2   267.2  4052.2   267.2  4102.2   266.5  4312.2   265.8  4772.2   263.2
  4817.7  262.42  4955.1  261.83  4979.7  263.25  4994.3  261.33  4998.4  260.03
    5000  259.87  5003.4  259.96  5005.7  261.38  5008.8  262.01  5072.2   263.9
  5142.2   265.1  5242.2   264.5  5402.2   266.7  5421.8   266.5  5673.7   269.8
#Mann= 8 , 1 , 0
  3492.2      .2       0  3492.2     .08       0  3963.1     .07       0
  4817.7     .15       0  4979.7     .06       0  5008.8     .15       0
  5421.8     .07       0  5673.7      .2       0
#XS Ineff= 2 , 0
       0    4008     267               0
Permanent Ineff=
       F       F
Bank Sta=4979.7,5008.8
XS Rating Curve= 0
Exp/Cntr=.3,.1

Type RM Length L Ch R = 1 ,28204.2 ,32.4,32.4,32.4
BEGIN DESCRIPTION:
Cross Section XS27
END DESCRIPTION:
XS GIS Cut Line= 2
    2945536.0348   13960436.0514    2945706.0541   13957642.8773
#Sta/Elev= 30
  3226.6   270.4  3606.9  268.79  3636.6   268.1  3896.6   267.1  4286.6   266.6
  4506.6   265.5  4516.6   264.7  4536.6   261.4  4569.4  263.64  4596.6   263.7
  4626.6   265.1  4804.9  264.88  4859.6  263.94  4954.2  263.76  4956.3  263.76
  4983.3  258.11  5000.1  257.22  5016.7  258.09  5023.7   262.9  5062.5  261.91
    5184  261.75  5196.6   262.9  5276.6   262.1  5346.6   263.9  5706.6   266.9
  5756.6   266.5  5786.6   268.5    5815  268.71  5936.6   268.4  6024.9   269.7
#Mann= 8 ,-1 , 0
  3226.6      .2       0  3606.9     .08       0  4569.4     .07       0
  4954.2     .15       0  4956.3     .06       0  5023.7     .15       0
    5815     .07       0  6024.9      .2       0
#XS Ineff= 2 , 0
       0    4625     266               0
Permanent Ineff=
       F       F
Bank Sta=4956.3,5023.7
XS Rating Curve= 0
Exp/Cntr=.5,.3

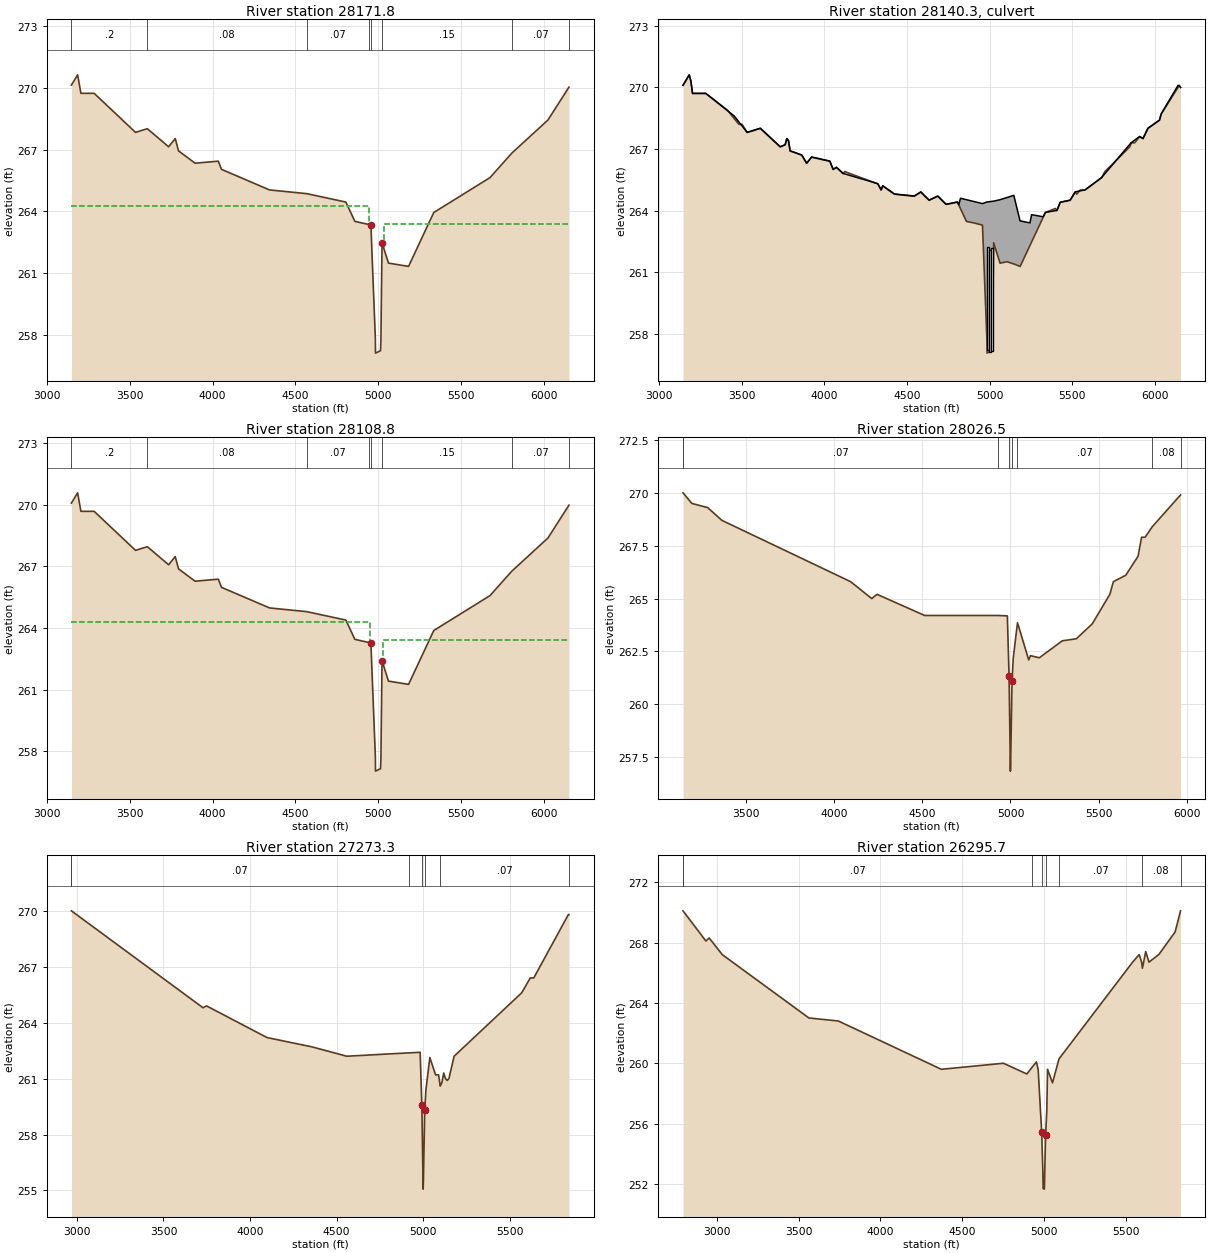
Type RM Length L Ch R = 1 ,28171.8 ,63,63,63
BEGIN DESCRIPTION:
Upstream Section of Bridge/Culvert/Weir
END DESCRIPTION:
XS GIS Cut Line= 4
    2945580.9458    13960518.598    2945664.2167   13958999.7577
    2945694.6546   13958240.2576     2945725.592   13957514.9315
#Sta/Elev= 30
  3146.2  270.14  3183.7  270.64  3203.7  269.74  3283.7  269.74  3533.7  267.84
  3604.9  268.02  3733.7  267.14  3773.7  267.54  3793.7  266.94  3893.7  266.34
  4033.7  266.44  4053.7  266.04  4343.7  265.04  4567.8  264.86  4804.9  264.45
  4859.6  263.51  4942.7  263.36  4956.3  263.33  4983.4   257.8  4984.1   257.1
  5014.5  257.22  5016.7  257.66  5023.7  262.47  5062.5  261.48    5184  261.32
  5336.3  263.94  5676.4  265.64  5808.1  266.83  6026.4  268.44  6153.4  270.04
#Mann= 8 , 1 , 0
  3146.2      .2       0  3604.9     .08       0  4567.8     .07       0
  4942.7     .15       0  4956.3     .06       0  5023.7     .15       0
  5808.1     .07       0  6153.4      .2       0
#XS Ineff= 2 , 0
       0  4946.3  264.28  5033.7       0   263.4
Permanent Ineff=
       F       F
Bank Sta=4956.3,5023.7
XS Rating Curve= 0
Exp/Cntr=.5,.3

Type RM Length L Ch R = 2 ,28140.3 ,,,
BEGIN DESCRIPTION:
VINING ROAD/STOKES
Structure ID: J158-00-00-03
END DESCRIPTION:
Bridge Culvert--1,0,-1,-1, 0
Deck Dist Width WeirC Skew NumUp NumDn MinLoCord MaxHiCord MaxSubmerge Is_Ogee
10,43,3,0, 60, 60, , , .95, 0, 1,1,,
  3146.2  3183.7  3193.7  3203.7  3283.7  3456.2  3533.7  3613.7  3733.7  3763.7
  3773.7  3783.7  3793.7  3863.7  3893.7  3923.7  4033.7  4053.7  4073.7  4113.7
  4323.7  4343.7  4353.7  4423.7  4543.7  4583.7  4633.7  4686.3  4736.3  4804.9
  4813.3  4823.3  4859.6  4956.3  4983.4  4984.1  5014.5  5016.7  5023.7  5062.5
  5145.8  5183.3  5243.3  5253.3  5323.3  5336.3  5406.3  5426.3  5486.4  5516.4
  5576.4  5676.4  5854.4  5906.4  5926.4  5956.4  6026.4  6036.4  6138.7  6153.4
   270.1  270.61  270.31  269.71  269.71   268.6  267.81  268.01  267.11  267.21
  267.51  267.41  266.91  266.71  266.31  266.61  266.41  266.01  266.11  265.81
  265.31  265.01  265.21  264.81  264.71  264.91  264.51  264.71  264.31  264.42
  264.28   264.6  264.53  264.34  264.42  264.42  264.45  264.45  264.46  264.53
  264.74   263.5   263.4   263.8   263.7  263.91  264.01  264.41  264.51  264.91
  265.01  265.61   267.3  267.61  267.51  268.01  268.41  268.71   270.1     270
   270.1   270.6   270.3   269.7   269.7  268.47   267.8     268   267.1   267.2
   267.5   267.4   266.9   266.7   266.3   266.6   266.4     266   266.1   265.8
   265.3     265   265.2   264.8   264.7   264.9   264.5   264.7   264.3  264.41
  264.27  264.09  263.47  263.29  257.76  257.06  257.18  257.62  262.43  261.44
   261.4  261.28   262.3  262.47  263.68   263.9     264   264.4   264.5   264.9
     265   265.6  267.26   267.6   267.5     268   268.4   268.7     270     270
  3146.2  3183.7  3193.7  3203.7  3283.7  3456.2  3533.7  3613.7  3733.7  3763.7
  3773.7  3783.7  3793.7  3863.7  3893.7  3923.7  4033.7  4053.7  4073.7  4113.7
  4323.7  4343.7  4353.7  4423.7  4543.7  4583.7  4633.7  4686.3  4736.3  4804.9
  4813.3  4823.3  4859.6  4956.3  4983.4  4984.1  5014.5  5016.7  5023.7  5062.5
  5145.8  5183.3  5243.3  5253.3  5323.3  5336.3  5406.3  5426.3  5486.4  5516.4
  5576.4  5676.4  5854.4  5906.4  5926.4  5956.4  6026.4  6036.4  6138.7  6153.4
   270.1  270.61  270.31  269.71  269.71   268.6  267.81  268.01  267.11  267.21
  267.51  267.41  266.91  266.71  266.31  266.61  266.41  266.01  266.11  265.81
  265.31  265.01  265.21  264.81  264.71  264.91  264.51  264.71  264.31  264.42
  264.28   264.6  264.53  264.34  264.42  264.42  264.45  264.45  264.46  264.53
  264.74   263.5   263.4   263.8   263.7  263.91  264.01  264.41  264.51  264.91
  265.01  265.61   267.3  267.61  267.51  268.01  268.41  268.71   270.1     270
   270.1   270.6   270.3   269.7   269.7  268.47   267.8     268   267.1   267.2
   267.5   267.4   266.9   266.7   266.3   266.6   266.4     266   266.1   265.8
   265.3     265   265.2   264.8   264.7   264.9   264.5   264.7   264.3  264.41
  264.27  264.09  263.47  263.29  257.76  257.06  257.18  257.62  262.43  261.44
   261.4  261.28   262.3  262.47  263.68   263.9     264   264.4   264.5   264.9
     265   265.6  267.26   267.6   267.5     268   268.4   268.7     270     270
BR Coef= 1 , 0 , 0 ,1.25, 0 ,,,.8,-1,2,1,
WSPro=,,,, 1 ,,,, 0 ,,,, 0 ,,,,-1 ,-1 ,-1 , 0 , 0 , 0 , 0 , 0
Culvert=2,5,10,43,.015,.5,1,8,1,257.22,4988.1,257.16,4988.1,Culvert #1  , 0 ,10
Culvert Bottom n=.015
Culvert=2,5,10,43,.015,.5,1,8,1,257.1,4999.9,257.15,4999.9,Culvert #2  , 0 ,10
Culvert Bottom n=.015
Culvert=2,5,10,43,.015,.5,1,8,1,257.17,5013,257.28,5013,Culvert #3  , 0 ,10
Culvert Bottom n=.015
BR U #Sta/Elev= 167
  3146.2   270.1  3156.2  270.23  3183.7   270.6  3193.7   270.3  3196.2  270.15
  3203.7   269.7  3216.2   269.7  3226.2   269.7  3256.2   269.7  3276.2   269.7
  3283.7   269.7  3336.2  269.38  3356.2  269.25  3413.7   268.9  3416.2  268.87
  3426.2  268.78  3456.2  268.47  3466.2  268.38  3483.7   268.2  3503.7   268.2
  3516.2  268.03  3533.7   267.8  3536.2  267.81  3546.2  267.83  3576.2  267.91
  3596.2  267.96  3604.9  267.98  3613.7     268  3616.2  267.98  3626.2  267.91
  3636.2  267.83  3716.2  267.23  3726.2  267.16  3733.7   267.1  3763.7   267.2
  3766.2  267.28  3773.7   267.5  3783.7   267.4  3786.2  267.28  3793.7   266.9
  3816.2  266.84  3836.2  266.78  3856.2  266.72  3863.7   266.7  3876.2  266.53
  3893.7   266.3  3906.2  266.43  3923.7   266.6  3986.2  266.49  4006.2  266.45
  4026.2  266.41  4033.7   266.4  4036.2  266.35  4046.2  266.15  4053.7     266
  4056.2  266.01  4073.7   266.1  4086.2  266.01  4113.7   265.8  4116.2  265.83
  4123.7   265.9  4136.2  265.86  4146.2  265.83  4166.2  265.77  4266.2  265.47
  4286.2  265.41  4316.2  265.32  4323.7   265.3  4343.7     265  4346.2  265.05
  4353.7   265.2  4356.2  265.19  4386.2  265.01  4423.7   264.8  4466.2  264.76
  4496.2  264.74  4506.2  264.73  4516.2  264.72  4526.2  264.71  4536.2  264.71
  4543.7   264.7  4566.2  264.81  4567.8  264.82  4583.7   264.9  4596.2   264.8
  4626.2  264.56  4633.7   264.5  4686.3   264.7  4693.3  264.64  4703.3  264.56
  4736.3   264.3  4763.3  264.34  4793.3  264.39  4803.3  264.41  4804.9  264.41
  4813.3  264.27  4823.3  264.09  4833.3  263.92  4859.6  263.47  4860.9  263.47
    4914  263.38  4914.6  263.38  4942.7  263.32  4956.3  263.29  4958.6  262.81
 4970.19  260.38  4970.3  260.36 4970.41  260.34  4983.3  257.64  4983.4  257.76
  4984.1  257.06  4993.4   257.1  5014.5  257.18  5016.7  257.62  5017.4  258.06
 5018.49  258.82  5018.6  258.89 5018.71  258.97    5019  259.17  5023.7  262.43
  5062.5  261.44  5063.7  261.44  5103.9  261.51  5104.1  261.51  5145.8   261.4
  5146.1   261.4  5183.3  261.28    5184  261.28  5243.3   262.3  5253.3  262.47
  5323.3  263.68  5333.3  263.85  5336.3   263.9  5353.3  263.96  5383.3  264.06
  5396.3   264.1  5406.3     264  5426.3   264.4  5486.4   264.5  5516.4   264.9
  5526.4   264.8  5546.4     265  5576.4     265  5594.4  265.11  5676.4   265.6
  5696.4   265.9  5724.4  266.12  5754.4  266.36  5808.1  266.79  5814.4  266.84
  5844.4  267.08  5846.4   267.1  5854.4  267.26  5856.4   267.3  5876.4   267.3
  5906.4   267.6  5926.4   267.5  5944.4   267.8  5956.4     268  6026.4   268.4
  6036.4   268.7  6054.4  268.93  6074.4  269.18  6104.4  269.57  6138.7     270
  6146.4   270.1  6153.4     270
BR U #Mann= 7
  3146.2      .2  3604.9     .08  4567.8     .07  4942.7     .15  4956.3     .05
  5023.7     .15  5808.1     .07
BR U Banks=4956.3,5023.7
BR D #Sta/Elev= 167
  3146.2   270.1  3156.2  270.23  3183.7   270.6  3193.7   270.3  3196.2  270.15
  3203.7   269.7  3216.2   269.7  3226.2   269.7  3256.2   269.7  3276.2   269.7
  3283.7   269.7  3336.2  269.38  3356.2  269.25  3413.7   268.9  3416.2  268.87
  3426.2  268.78  3456.2  268.47  3466.2  268.38  3483.7   268.2  3503.7   268.2
  3516.2  268.03  3533.7   267.8  3536.2  267.81  3546.2  267.83  3576.2  267.91
  3596.2  267.96  3604.9  267.98  3613.7     268  3616.2  267.98  3626.2  267.91
  3636.2  267.83  3716.2  267.23  3726.2  267.16  3733.7   267.1  3763.7   267.2
  3766.2  267.28  3773.7   267.5  3783.7   267.4  3786.2  267.28  3793.7   266.9
  3816.2  266.84  3836.2  266.78  3856.2  266.72  3863.7   266.7  3876.2  266.53
  3893.7   266.3  3906.2  266.43  3923.7   266.6  3986.2  266.49  4006.2  266.45
  4026.2  266.41  4033.7   266.4  4036.2  266.35  4046.2  266.15  4053.7     266
  4056.2  266.01  4073.7   266.1  4086.2  266.01  4113.7   265.8  4116.2  265.83
  4123.7   265.9  4136.2  265.86  4146.2  265.83  4166.2  265.77  4266.2  265.47
  4286.2  265.41  4316.2  265.32  4323.7   265.3  4343.7     265  4346.2  265.05
  4353.7   265.2  4356.2  265.19  4386.2  265.01  4423.7   264.8  4466.2  264.76
  4496.2  264.74  4506.2  264.73  4516.2  264.72  4526.2  264.71  4536.2  264.71
  4543.7   264.7  4566.2  264.81  4567.8  264.82  4583.7   264.9  4596.2   264.8
  4626.2  264.56  4633.7   264.5  4686.3   264.7  4693.3  264.64  4703.3  264.56
  4736.3   264.3  4763.3  264.34  4793.3  264.39  4803.3  264.41  4804.9  264.41
  4813.3  264.27  4823.3  264.09  4833.3  263.92  4859.6  263.47  4860.9  263.47
    4914  263.38  4914.6  263.38  4942.7  263.32  4956.3  263.29  4958.6  262.81
 4970.19  260.38  4970.3  260.36 4970.41  260.34  4983.3  257.64  4983.4  257.76
  4984.1  257.06  4993.4   257.1  5014.5  257.18  5016.7  257.62  5017.4  258.06
 5018.49  258.82  5018.6  258.89 5018.71  258.97    5019  259.17  5023.7  262.43
  5062.5  261.44  5063.7  261.44  5103.9  261.51  5104.1  261.51  5145.8   261.4
  5146.1   261.4  5183.3  261.28    5184  261.28  5243.3   262.3  5253.3  262.47
  5323.3  263.68  5333.3  263.85  5336.3   263.9  5353.3  263.96  5383.3  264.06
  5396.3   264.1  5406.3     264  5426.3   264.4  5486.4   264.5  5516.4   264.9
  5526.4   264.8  5546.4     265  5576.4     265  5594.4  265.11  5676.4   265.6
  5696.4   265.9  5724.4  266.12  5754.4  266.36  5808.1  266.79  5814.4  266.84
  5844.4  267.08  5846.4   267.1  5854.4  267.26  5856.4   267.3  5876.4   267.3
  5906.4   267.6  5926.4   267.5  5944.4   267.8  5956.4     268  6026.4   268.4
  6036.4   268.7  6054.4  268.93  6074.4  269.18  6104.4  269.57  6138.7     270
  6146.4   270.1  6153.4     270
BR D #Mann= 7
  3146.2      .2  3604.9     .08  4567.8     .07  4942.7     .15  4956.3     .05
  5023.7     .15  5808.1     .07
BR D Banks=4956.3,5023.7
BC Design=,, 0 ,, 0 ,,,,,,

Type RM Length L Ch R = 1 ,28108.8 ,82.3,82.3,82.3
BEGIN DESCRIPTION:
Downstream Section of Bridge/Culvert/Weir
END DESCRIPTION:
XS GIS Cut Line= 4
    2945640.3895   13960517.4667    2945720.0652    13959002.424
    2945756.3978   13958232.1725    2945788.9667   13957513.9054
#Sta/Elev= 30
  3146.2  270.08  3183.7  270.58  3203.7  269.68  3283.7  269.68  3533.7  267.78
  3604.9  267.96  3733.7  267.08  3773.7  267.48  3793.7  266.88  3893.7  266.28
  4033.7  266.38  4053.7  265.98  4343.7  264.98  4567.8   264.8  4804.9  264.39
  4859.6  263.45  4942.7   263.3  4956.3  263.27  4983.4  257.74  4984.1  257.04
  5014.5  257.16  5016.7   257.6  5023.7  262.41  5062.5  261.42    5184  261.26
  5336.3  263.88  5676.4  265.58  5808.1  266.77  6026.4  268.38  6153.4  269.98
#Mann= 8 , 1 , 0
  3146.2      .2       0  3604.9     .08       0  4567.8     .07       0
  4942.7     .15       0  4956.3     .06       0  5023.7     .15       0
  5808.1     .07       0  6153.4      .2       0
#XS Ineff= 2 , 0
       0 4949.63  264.28 5030.37       0   263.4
Permanent Ineff=
       F       F
Bank Sta=4956.3,5023.7
XS Rating Curve= 0
Exp/Cntr=.5,.3

Type RM Length L Ch R = 1 ,28026.5 ,625.17,753.2,797.22
BEGIN DESCRIPTION:
Cross Section XS26
END DESCRIPTION:
XS GIS Cut Line= 2
    2945730.3426   13960525.1091    2945867.9772   13957707.6466
#Sta/Elev= 30
  3143.3     270  3193.3   269.5  3283.3   269.3  3363.3   268.7  4093.3   265.8
  4213.3     265  4243.3   265.2  4513.3   264.2  4928.7   264.2  4982.2  264.18
  4991.9  261.33  4999.5  256.84    5001  257.31  5008.7  261.08  5015.6  262.18
  5039.7  263.86  5103.3   262.1  5113.3   262.3  5163.3   262.2  5293.3     263
  5373.3   263.1  5463.3   263.8  5563.3   265.2  5583.3   265.8  5653.3   266.1
  5723.3     267  5743.3   267.9  5763.3   267.9  5803.1  268.39  5964.1   269.9
#Mann= 8 , 1 , 0
  3143.3      .2       0  3143.3     .07       0  4928.7     .15       0
  4991.9     .06       0  5008.7     .15       0  5039.7     .07       0
  5803.1     .08       0  5964.1      .2       0
Bank Sta=4991.9,5008.7
XS Rating Curve= 0
Exp/Cntr=.3,.1

Type RM Length L Ch R = 1 ,27273.3 ,967.38,977.6,991.22
BEGIN DESCRIPTION:
Cross Section XS25
END DESCRIPTION:
XS GIS Cut Line= 2
    2945795.1118   13960654.6476    2946871.9007   13957991.0121
#Sta/Elev= 29
  2968.3     270  3728.3   264.8  3748.3   264.9  4098.3   263.2  4358.3   262.7
  4558.3   262.2  4916.8  262.38  4982.2  262.41  4991.9  259.56  4999.5  255.07
    5001  255.54  5008.7  259.31  5015.6  260.41  5038.1  262.13  5071.2   261.2
  5088.3   261.2  5096.2  260.73  5098.3   260.6  5108.3   260.8  5118.3   261.3
  5128.3     261  5138.3   260.9  5148.3     261  5178.3   262.2  5568.3   265.6
  5618.3   266.4  5638.3   266.4  5838.3   269.8  5841.4   269.8
#Mann= 7 , 1 , 0
  2968.3      .2       0  2968.3     .07       0  4916.8     .15       0
  4991.9     .06       0  5008.7     .15       0  5096.2     .07       0
  5841.4      .2       0
Bank Sta=4991.9,5008.7
XS Rating Curve= 0
Exp/Cntr=.3,.1

Type RM Length L Ch R = 1 ,26295.7 ,923.94,927.4,925.59
BEGIN DESCRIPTION:
Cross Section XS24
END DESCRIPTION:
XS GIS Cut Line= 2
    2946548.0544   13961326.6286    2947697.7087   13958509.1661
#Sta/Elev= 30
  2793.4   270.1  2933.4   268.1  2953.4   268.3  3033.4   267.2  3563.4     263
  3743.4   262.8  4373.4   259.6  4753.4     260  4896.3  259.29  4929.7  259.75
    4955  260.09  4965.7  259.58    4987  255.45  4993.7  253.08  4996.2   251.7
  5003.6  251.66  5011.1  255.23  5018.5  256.88  5022.9   259.6  5053.4   258.7
  5093.1  260.29  5543.4   266.7  5583.4   267.2  5598.5  266.69  5603.4   266.3
  5623.4   267.4  5643.4   266.7  5703.4   267.2  5803.4   268.7  5836.4   270.1
#Mann= 8 , 1 , 0
  2793.4      .2       0  2793.4     .07       0  4929.7     .15       0
    4987     .06       0  5011.1     .15       0  5093.1     .07       0
  5598.5     .08       0  5836.4      .2       0
Bank Sta=4987,5011.1
XS Rating Curve= 0
Exp/Cntr=.3,.1

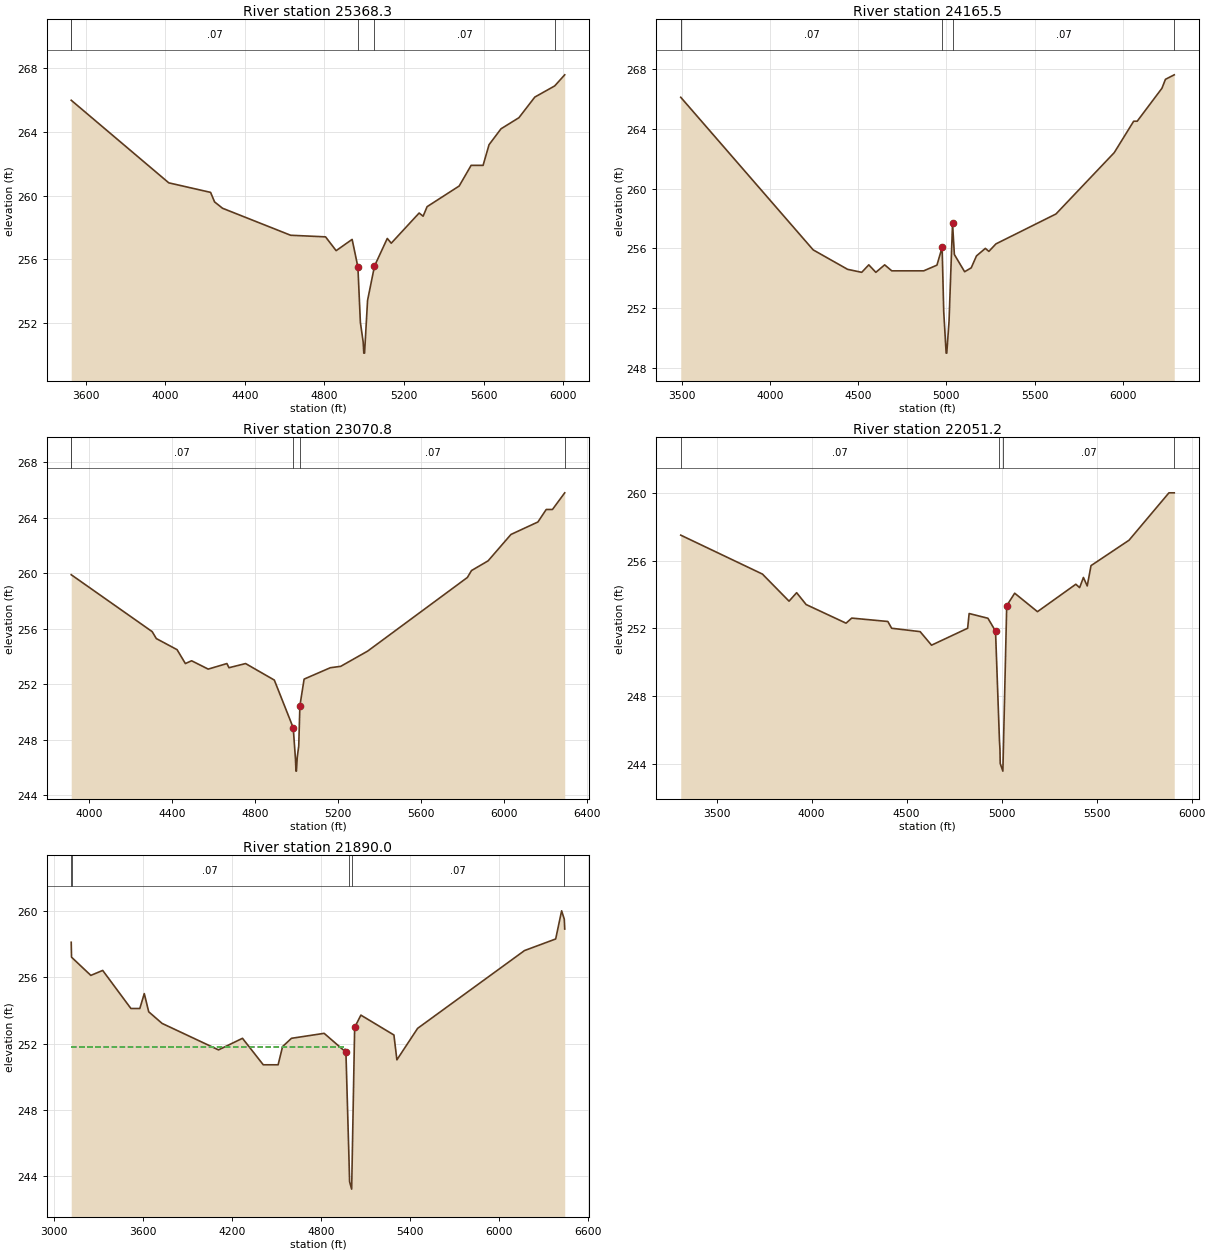
Type RM Length L Ch R = 1 ,25368.3 ,1280.22,1202.8,1147.78
BEGIN DESCRIPTION:
Cross Section XS23
END DESCRIPTION:
XS GIS Cut Line= 5
    2948159.1896   13961132.3209    2948110.6127   13960031.2436
    2948110.6127   13959925.9935    2948345.4012    13959383.551
     2948337.305   13958703.4739
#Sta/Elev= 30
  3528.2     266  4018.2   260.8  4228.2   260.2  4248.2   259.6  4288.2   259.2
  4630.3   257.5  4805.6   257.4  4858.8  256.53  4939.1  257.24  4968.1   255.5
  4980.5  252.02  4994.5  250.78  4997.7  250.08  5001.5  250.08  5016.6   253.4
  5051.4  255.56  5115.6   257.3  5135.6     257  5275.6   258.9  5295.6   258.7
  5315.6   259.3  5476.7   260.6  5536.7   261.9  5596.7   261.9  5626.7   263.2
  5686.7   264.2  5776.7   264.9  5856.7   266.2  5956.3   266.9  6006.8   267.6
#Mann= 5 , 1 , 0
  3528.2      .2       0  3528.2     .07       0  4968.1     .06       0
  5051.4     .07       0  5956.3     .08       0
Bank Sta=4968.1,5051.4
XS Rating Curve= 0
Exp/Cntr=.3,.1

Type RM Length L Ch R = 1 ,24165.5 ,1148.43,1094.7,1066.34
BEGIN DESCRIPTION:
Cross Section XS22
END DESCRIPTION:
XS GIS Cut Line= 3
    2948700.3087   13961459.4819    2949268.2073    13960729.503
    2949414.0939    13958865.397
#Sta/Elev= 30
  3495.6   266.1  4245.6   255.9  4440.5   254.6  4520.5   254.4  4560.5   254.9
  4600.5   254.4  4650.5   254.9  4690.5   254.5  4871.4   254.5  4946.5  254.88
  4975.8  256.07  4984.9  251.77  4998.6     249  5002.1     249    5015  251.14
  5034.8  257.67  5045.1  255.59  5103.2  254.44  5140.5   254.7  5170.5   255.5
  5220.5     256  5240.5   255.8  5280.5   256.3  5620.5   258.3  5950.5   262.4
  6060.5   264.5  6080.5   264.5  6220.5   266.7  6240.5   267.3  6290.3   267.6
#Mann= 5 , 1 , 0
  3495.6      .2       0  3495.6     .07       0  4975.8     .06       0
  5034.8     .07       0  6290.3      .2       0
Bank Sta=4975.8,5034.8
XS Rating Curve= 0
Exp/Cntr=.3,.1

Type RM Length L Ch R = 1 ,23070.8 ,839.74,1019.6,974.6
BEGIN DESCRIPTION:
Cross Section XS21
END DESCRIPTION:
XS GIS Cut Line= 3
     2950528.969    13961099.328    2950375.0743   13959860.4757
    2949898.0008    13958837.076
#Sta/Elev= 30
  3915.4   259.9  4305.4   255.8  4325.4   255.3  4425.4   254.5  4465.4   253.5
  4495.4   253.7  4575.4   253.1  4665.4   253.5  4675.4   253.2  4755.4   253.5
  4893.9  252.31    4985  248.87  4995.7  246.63  4998.3  245.75  5000.4  245.75
  5004.3  246.75  5011.5  247.56  5017.1  250.46  5037.4  252.38  5163.8   253.2
  5213.8   253.3  5343.8   254.4  5823.8   259.7  5843.8   260.2  5923.8   260.9
  6033.8   262.8  6163.8   263.7  6203.8   264.6  6233.8   264.6  6292.9   265.8
#Mann= 5 , 1 , 0
  3915.4      .2       0  3915.4     .07       0    4985     .06       0
  5017.1     .07       0  6292.9      .2       0
Bank Sta=4985,5017.1
XS Rating Curve= 0
Exp/Cntr=.3,.1

Type RM Length L Ch R = 1 ,22051.2 ,110.01,161.2,251.96
BEGIN DESCRIPTION:
Cross Section XS20
END DESCRIPTION:
XS GIS Cut Line= 3
     2950968.556   13960954.2054    2951065.7099   13959407.8395
    2950863.3059   13958379.6276
#Sta/Elev= 30
    3311   257.5    3741   255.2    3881   253.6    3921   254.1    3971   253.4
    4181   252.3    4211   252.6    4401   252.4    4421     252    4571   251.8
    4631     251    4821     252  4828.9  252.87  4927.8  252.59  4967.8  251.83
  4988.5  245.36  4991.2  244.84  4992.5  244.01  5006.4  243.56  5026.6  253.33
  5068.6  254.07  5188.5  252.98  5390.4   254.6  5410.4   254.4  5430.4     255
  5450.4   254.5  5470.4   255.7  5670.4   257.2  5880.4     260  5908.4     260
#Mann= 4 ,-1 , 0
    3311     .07       0  4988.5     .06       0  5008.7     .07       0
  5908.4      .2       0
Bank Sta=4967.8,5026.6
XS Rating Curve= 0
Exp/Cntr=.5,.3

Type RM Length L Ch R = 1 ,21890.0 ,58,58,58
BEGIN DESCRIPTION:
Upstream Section of Bridge/Culvert/Weir
END DESCRIPTION:
XS GIS Cut Line= 4
    2951054.4416   13961031.1045     2951110.512   13959969.1836
     2951169.463   13958781.0959    2951209.3263   13957710.7898
#Sta/Elev= 30
  3117.5  258.12  3119.6  257.22  3249.6  256.12  3329.6  256.42  3519.6  254.12
  3579.6  254.12  3609.6  255.02  3639.6  253.92  3729.6  253.22  4109.6  251.62
  4271.1  252.32  4411.1  250.72  4511.1  250.72  4541.1  251.82  4601.1  252.32
  4821.1  252.62  4967.8  251.48  4988.5  245.01  4992.5  243.66  5006.4  243.21
  5026.6  252.98  5068.6  253.72  5291.1  252.52  5311.1  251.02  5450.6  252.92
  6170.6  257.62  6380.6  258.32  6420.6  260.02  6438.5  259.52  6441.5  258.92
#Mann= 5 ,-1 , 0
  3117.5      .2       0  3119.6     .07       0  4988.5     .06       0
  5008.7     .07       0  6438.5      .2       0
#XS Ineff= 2 , 0
       0  4958.3   251.8  5036.6       0   251.8
Permanent Ineff=
       F       F
Bank Sta=4967.8,5026.6
XS Rating Curve= 0
Exp/Cntr=.5,.3