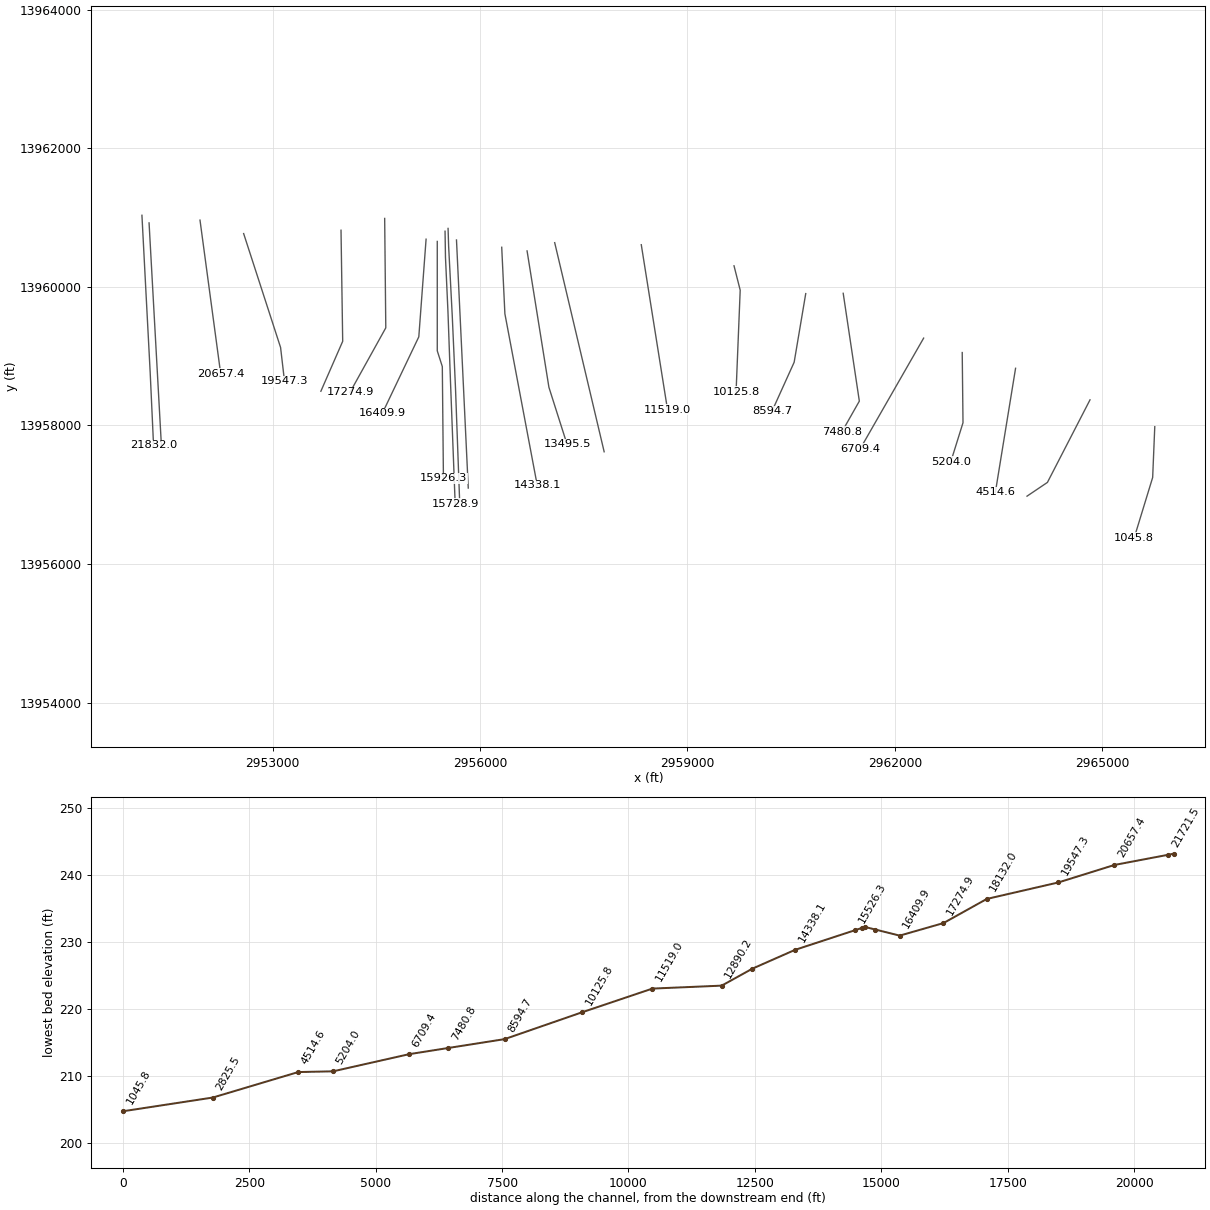
HEC-RAS study J158-00-00.PRJ: J158-00-00

--- J158-00-00.g01 (geometry) --- (continued)

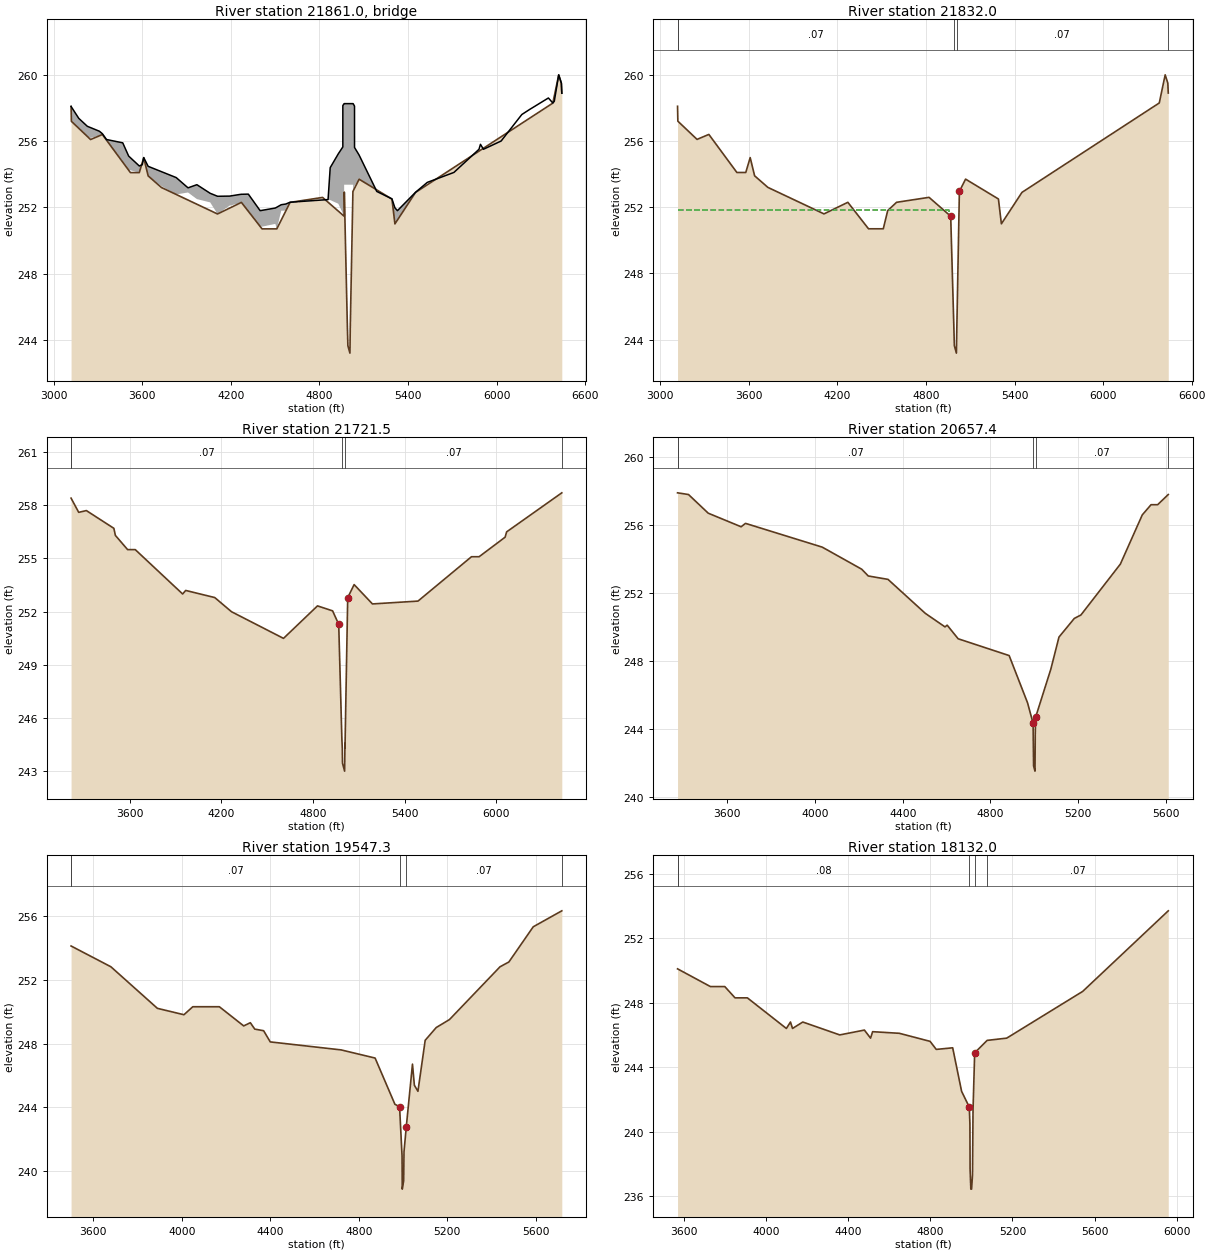
Type RM Length L Ch R = 3 ,21861.0 ,,,
BEGIN DESCRIPTION:
BINFORD
Structure ID: J158-00-00-02
END DESCRIPTION:
Bridge Culvert--1,0,-1,-1, 0
Deck Dist Width WeirC Skew NumUp NumDn MinLoCord MaxHiCord MaxSubmerge Is_Ogee
10,38,2.6,0, 60, 60, , , .95, 0, 1,1,,
  3117.5  3119.6  3169.6  3227.5  3309.6  3329.6  3357.5  3467.5  3507.5  3579.6
  3599.6  3609.6  3639.6  3829.6  3909.6  3969.6  4059.6  4109.6  4191.1  4261.1
  4271.1  4318.2  4398.2  4501.1  4511.1  4541.1  4571.1  4601.1  4858.2  4872.7
  4927.8 4958.19  4958.3  4967.1 4967.21  4967.3 5027.89    5028  5037.4 5037.51
  5068.6  5188.5  5291.1  5311.1  5328.2  5450.6  5530.6  5710.6  5880.6  5890.6
  5910.6  6030.6  6170.6  6222.4  6350.6  6380.6  6390.6  6420.6  6438.5  6441.5
   258.1  258.07  257.38   256.9   256.6  256.45   256.1   255.9   255.1   254.5
  254.58  255.01  254.48   253.8  253.18  253.37  252.85  252.67  252.68  252.78
  252.79   252.8   251.8  251.96  252.01  252.16   252.2  252.31  252.47   254.4
  255.24  255.65  258.15  258.27  258.27  258.27  258.27  258.27  258.12  255.62
  255.16  252.96  252.51  251.97   251.8  252.91  253.51  254.11  255.51  255.81
  255.51  256.01  257.61  257.91  258.61  258.31  258.41  260.01  259.51   258.9
   258.1   257.2   256.7  256.23   256.1   256.4  256.04  254.78  254.27   254.1
   254.5     255   253.9   252.6   252.9   252.5   252.3   251.6   252.1     252
   252.3  251.46  250.81     251   250.7   251.8   251.8   252.3  252.46  252.44
  252.22  251.64  251.64  251.47  251.47  253.37  253.37     253   253.3   253.3
   253.7  252.61   252.5     251  251.17   252.9   253.5   254.1   255.5   255.8
   255.5     256   257.6   257.9   258.6   258.3   258.4     260   259.5   258.9
  3117.5  3119.6  3169.6  3227.5  3309.6  3329.6  3357.5  3467.5  3507.5  3579.6
  3599.6  3609.6  3639.6  3829.6  3909.6  3969.6  4059.6  4109.6  4191.1  4261.1
  4271.1  4318.2  4398.2  4501.1  4511.1  4541.1  4571.1  4601.1  4858.2  4872.7
  4927.8 4958.19  4958.3  4967.1 4967.21  4967.3 5027.89    5028  5037.4 5037.51
  5068.6  5188.5  5291.1  5311.1  5328.2  5450.6  5530.6  5710.6  5880.6  5890.6
  5910.6  6030.6  6170.6  6222.4  6350.6  6380.6  6390.6  6420.6  6438.5  6441.5
   258.1  258.07  257.38   256.9   256.6  256.45   256.1   255.9   255.1   254.5
  254.58  255.01  254.48   253.8  253.18  253.37  252.85  252.67  252.68  252.78
  252.79   252.8   251.8  251.96  252.01  252.16   252.2  252.31  252.47   254.4
  255.24  255.65  258.15  258.27  258.27  258.27  258.27  258.27  258.12  255.62
  255.16  252.96  252.51  251.97   251.8  252.91  253.51  254.11  255.51  255.81
  255.51  256.01  257.61  257.91  258.61  258.31  258.41  260.01  259.51   258.9
   258.1   257.2   256.7  256.23   256.1   256.4  256.04  254.78  254.27   254.1
   254.5     255   253.9   252.6   252.9   252.5   252.3   251.6   252.1     252
   252.3  251.46  250.81     251   250.7   251.8   251.8   252.3  252.46  252.44
  252.22  251.64  251.64  251.47  251.47  253.37  253.37     253   253.3   253.3
   253.7  252.61   252.5     251  251.17   252.9   253.5   254.1   255.5   255.8
   255.5     256   257.6   257.9   258.6   258.3   258.4     260   259.5   258.9
Abutment Skew #Up #Dn= , 2 , 2
  4967.1 4968.29
  253.37  252.92
  4967.1 4968.29
  253.37  252.92
Abutment Skew #Up #Dn= , 2 , 2
  5026.7 5028.09
  252.96  253.37
  5026.7 5028.09
  252.96  253.37
BR Coef= 1 , 1 , 0 ,1.25, 0 ,,,.8,-1,2,0,
WSPro=,,,, 1 ,,,, 0 ,,,, 0 ,,,,-1 ,-1 ,-1 , 0 , 0 , 0 , 0 , 0
BR U #Sta/Elev= 30
  3117.5   258.1  3119.6   257.2  3249.6   256.1  3329.6   256.4  3519.6   254.1
  3579.6   254.1  3609.6     255  3639.6   253.9  3729.6   253.2  4109.6   251.6
  4271.1   252.3  4411.1   250.7  4511.1   250.7  4601.1   252.3  4821.1   252.6
  4967.8  251.46  4968.3  252.92  4988.5  244.99  4992.5  243.64  5006.4  243.19
  5008.7  244.75  5026.6  252.96  5068.6   253.7  5291.1   252.5  5311.1     251
  5450.6   252.9  6380.6   258.3  6420.6     260  6438.5   259.5  6441.5   258.9
BR U #Mann= 5
  3117.5      .2  3119.6     .07  4988.5     .05  5008.7     .07  6438.5      .2
BR U Banks=4967.8,5026.6
BR D #Sta/Elev= 30
  3117.5   258.1  3119.6   257.2  3249.6   256.1  3329.6   256.4  3519.6   254.1
  3579.6   254.1  3609.6     255  3639.6   253.9  3729.6   253.2  4109.6   251.6
  4271.1   252.3  4411.1   250.7  4511.1   250.7  4601.1   252.3  4821.1   252.6
  4967.8  251.46  4968.3  252.92  4988.5  244.99  4992.5  243.64  5006.4  243.19
  5008.7  244.75  5026.6  252.96  5068.6   253.7  5291.1   252.5  5311.1     251
  5450.6   252.9  6380.6   258.3  6420.6     260  6438.5   259.5  6441.5   258.9
BR D #Mann= 5
  3117.5      .2  3119.6     .07  4988.5     .05  5008.7     .07  6438.5      .2
BR D Banks=4967.8,5026.6
BC Design=,, 0 ,, 0 ,,,,,,

Type RM Length L Ch R = 1 ,21832.0 ,110.5,110.5,110.5
BEGIN DESCRIPTION:
Downstream Section of Bridge/Culvert/Weir
END DESCRIPTION:
XS GIS Cut Line= 4
    2951108.2175   13961032.1476    2951164.2166   13959962.9368
    2951227.2218   13958770.3384    2951276.3321    13957712.445
#Sta/Elev= 30
  3117.5  258.09  3119.6  257.19  3249.6  256.09  3329.6  256.39  3519.6  254.09
  3579.6  254.09  3609.6  254.99  3639.6  253.89  3729.6  253.19  4109.6  251.59
  4271.1  252.29  4411.1  250.69  4511.1  250.69  4541.1  251.79  4601.1  252.29
  4821.1  252.59  4967.8  251.45  4988.5  244.98  4992.5  243.63  5006.4  243.18
  5008.9   244.5  5026.6  252.95  5068.6  253.69  5291.1  252.49  5311.1  250.99
  5450.6  252.89  6380.6  258.29  6420.6  259.99  6438.5  259.49  6441.5  258.89
#Mann= 5 ,-1 , 0
  3117.5      .2       0  3119.6     .07       0  4988.5     .06       0
  5008.9     .07       0  6438.5      .2       0
#XS Ineff= 2 , 0
       0  4958.3   251.8  5036.6       0   251.8
Permanent Ineff=
       F       F
Bank Sta=4967.8,5026.6
XS Rating Curve= 0
Exp/Cntr=.5,.3

Type RM Length L Ch R = 1 ,21721.5 ,855.91,1064.1,914.94
BEGIN DESCRIPTION:
Cross Section XS19
END DESCRIPTION:
XS GIS Cut Line= 2
    2951211.4407   13960921.8208    2951389.5561   13957715.7427
#Sta/Elev= 30
  3216.5   258.4  3266.5   257.6  3316.5   257.7  3496.5   256.7  3506.5   256.3
  3586.5   255.5  3636.5   255.5  3946.5     253  3966.5   253.2  4156.5   252.8
  4266.5     252  4606.5   250.5  4828.9  252.33  4927.8  252.05  4967.8  251.29
  4988.5  244.82  4991.2   244.3  4992.5  243.47  5006.4  243.02  5008.7  244.58
  5008.9  244.34  5026.6  252.79  5068.6  253.53  5188.5  252.44  5486.5   252.6
  5836.5   255.1  5886.5   255.1  6056.5   256.2  6066.5   256.5  6427.5   258.7
#Mann= 5 , 1 , 0
  3216.5      .2       0  3216.5     .07       0  4988.5     .06       0
  5008.7     .07       0  6427.5      .2       0
Bank Sta=4967.8,5026.6
XS Rating Curve= 0
Exp/Cntr=.3,.1

Type RM Length L Ch R = 1 ,20657.4 ,821.32,1110.1,972.62
BEGIN DESCRIPTION:
Cross Section XS18
END DESCRIPTION:
XS GIS Cut Line= 2
    2951948.1909   13960962.3016    2952247.7487   13958743.9546
#Sta/Elev= 30
  3372.8   257.9  3422.8   257.8  3512.8   256.7  3662.8   255.9  3682.8   256.1
  4032.8   254.7  4212.8   253.4  4242.8     253  4332.8   252.8  4502.8   250.8
  4592.8     250  4602.8   250.1  4652.8   249.3  4885.5  248.31  4969.3  245.53
  4994.9  244.31  4995.4   243.5    4997   241.8  5003.4   241.5  5004.6  243.72
  5006.3  244.68  5075.6  247.51  5112.8   249.4  5182.8   250.5  5212.8   250.7
  5392.8   253.7  5492.8   256.6  5532.8   257.2  5562.8   257.2  5611.3   257.8
#Mann= 5 , 1 , 0
  3372.8      .2       0  3372.8     .07       0  4994.9     .06       0
  5006.3     .07       0  5611.3      .2       0
Bank Sta=4994.9,5006.3
XS Rating Curve= 0
Exp/Cntr=.3,.1

Type RM Length L Ch R = 1 ,19547.3 ,1234.23,1415.3,997.26
BEGIN DESCRIPTION:
Cross Section XS17
END DESCRIPTION:
XS GIS Cut Line= 3
    2952579.6912   13960767.9938    2953114.0375    13959124.474
    2953170.7106   13958638.7046
#Sta/Elev= 30
  3500.1   254.1  3680.1   252.8  3890.1   250.2  4010.1   249.8  4050.1   250.3
  4170.1   250.3  4280.1   249.1  4310.1   249.3  4330.1   248.9  4370.1   248.8
  4400.1   248.1  4720.1   247.6  4873.8  247.09  4963.3   244.2  4984.4  244.04
  4995.6  240.97  4996.5  238.89  5002.9  239.42  5004.4  241.23  5014.8   242.8
  5042.7  246.71  5051.2  245.39  5067.4  245.01  5100.1   248.2  5150.1     249
  5210.1   249.5  5438.3   252.8  5478.3   253.1  5588.3   255.3  5717.4   256.3
#Mann= 5 , 1 , 0
  3500.1      .2       0  3500.1     .07       0  4984.4     .06       0
  5014.8     .07       0  5717.4      .2       0
Bank Sta=4984.4,5014.8
XS Rating Curve= 0
Exp/Cntr=.3,.1

Type RM Length L Ch R = 1 ,18132.0 ,628.64,857.1,596.97
BEGIN DESCRIPTION:
Cross Section XS16
END DESCRIPTION:
XS GIS Cut Line= 3
    2953988.4224   13960816.5708    2954012.7109   13959213.5317
    2953696.9608   13958492.9738
#Sta/Elev= 30
  3569.3   250.1  3729.3     249  3799.3     249  3849.3   248.3  3909.3   248.3
  4099.3   246.4  4119.3   246.8  4129.3   246.4  4179.3   246.8  4359.3     246
  4479.3   246.3  4509.3   245.8  4519.3   246.2  4649.3   246.1  4799.3   245.6
  4829.3   245.1  4909.3   245.2  4952.7   242.5  4990.2  241.52  4993.2  240.47
  4994.1  237.67  4997.7  236.43  5001.4  236.43  5005.8  237.32  5008.4  241.37
  5016.4  244.89  5077.2  245.66  5172.5   245.8  5542.5   248.7  5959.2   253.7
#Mann= 5 , 1 , 0
  3569.3      .2       0  3569.3     .08       0  4990.2     .07       0
  5016.4     .08       0  5077.2     .07       0
Bank Sta=4990.2,5016.4
XS Rating Curve= 0
Exp/Cntr=.3,.1

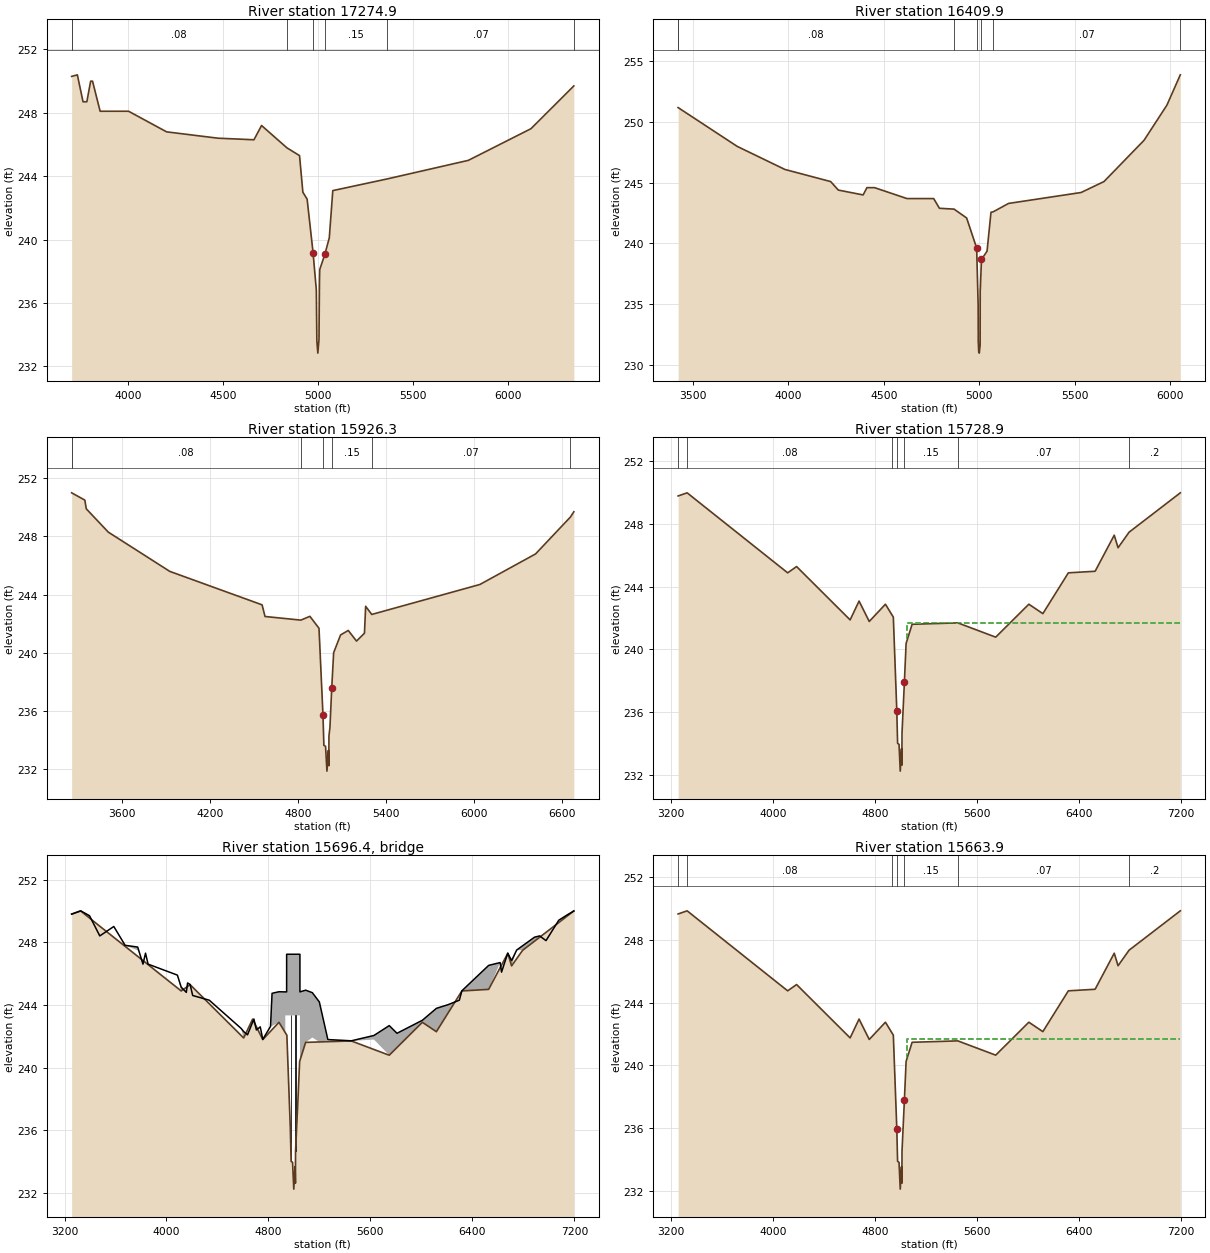
Type RM Length L Ch R = 1 ,17274.9 ,714.3,865,534.46
BEGIN DESCRIPTION:
Cross Section XS15
END DESCRIPTION:
XS GIS Cut Line= 3
    2954619.9227   13960986.5901     2954636.115   13959407.8395
    2954117.9609   13958476.7815
#Sta/Elev= 30
  3703.1   250.3  3733.1   250.4  3763.1   248.7  3783.1   248.7  3803.1     250
  3813.1     250  3853.1   248.1  4003.1   248.1  4203.1   246.8  4473.1   246.4
  4663.1   246.3  4703.1   247.2  4836.8  245.79  4903.1   245.3  4920.6  242.99
  4943.1  242.55  4974.4  239.17  4991.5  236.82  4994.3  233.61  4999.4  232.83
  5005.6  233.69  5008.1  237.47  5009.5  238.11  5036.3  239.06  5059.8  240.11
  5078.2  243.09  5365.4  243.83  5791.9     245  6121.9     247  6347.5   249.7
#Mann= 7 , 1 , 0
  3703.1      .2       0  3703.1     .08       0  4836.8     .15       0
  4974.4     .07       0  5036.3     .15       0  5365.4     .07       0
  6347.5      .2       0
Bank Sta=4974.4,5036.3
XS Rating Curve= 0
Exp/Cntr=.3,.1

Type RM Length L Ch R = 1 ,16409.9 ,289.97,483.6,564.71
BEGIN DESCRIPTION:
Cross Section XS14
END DESCRIPTION:
XS GIS Cut Line= 3
    2955219.0383   13960687.0323    2955113.7882    13959278.301
     2954587.538   13958177.2237
#Sta/Elev= 30
  3421.4   251.2  3731.4     248  3981.4   246.1  4221.4   245.1  4261.4   244.4
  4391.4     244  4411.4   244.6  4451.4   244.6  4621.4   243.7  4761.4   243.7
  4791.4   242.9  4868.4  242.83  4934.1   242.1  4986.7  239.62  4994.6  234.85
  4995.1  231.96  4997.5  231.06  5000.4  230.96  5004.9  231.61  5005.3  236.05
    5012  238.68  5041.1  239.36  5061.8  242.57  5073.6  242.61  5154.1   243.3
  5534.1   244.2  5654.1   245.1  5864.1   248.5  5984.1   251.4  6054.4   253.9
#Mann= 7 , 1 , 0
  3421.4      .2       0  3421.4     .08       0  4868.4     .15       0
  4986.7     .07       0    5012     .15       0  5073.6     .07       0
  6054.4      .2       0
Bank Sta=4986.7,5012
XS Rating Curve= 0
Exp/Cntr=.3,.1

Type RM Length L Ch R = 1 ,15926.3 ,174.97,197.4,119.69
BEGIN DESCRIPTION:
Cross Section XS13
END DESCRIPTION:
XS GIS Cut Line= 4
    2955380.9614   13960654.6476    2955380.9614   13959075.8971
    2955453.8268   13958849.2047    2955470.0191   13957238.0695
#Sta/Elev= 30
  3256.1     251  3346.1   250.5  3356.1   249.9  3506.1   248.3  3926.1   245.6
  4556.1   243.3  4576.1   242.5  4820.8  242.25  4882.5  242.51  4944.6  241.69
  4971.7  235.73  4977.9  233.64  4989.3  233.58  4998.8  231.87  5008.8   233.3
  5011.6  232.25  5012.5  234.29  5019.2  234.86  5031.3  237.55  5044.6  240.01
  5091.8  241.23  5144.3  241.54  5200.7  240.81  5254.9  241.35    5263   243.2
  5304.7  242.64    6043   244.7    6423   246.8  6661.2  249.34  6684.2   249.7
#Mann= 7 , 1 , 0
  3256.1      .2       0  3256.1     .08       0  4820.8     .15       0
  4971.7     .07       0  5031.3     .15       0  5304.7     .07       0
  6661.2      .2       0
Bank Sta=4971.7,5031.3
XS Rating Curve= 0
Exp/Cntr=.5,.3

Type RM Length L Ch R = 1 ,15728.9 ,65,65,65
BEGIN DESCRIPTION:
Upstream Section of Bridge/Culvert/Weir
END DESCRIPTION:
XS GIS Cut Line= 5
    2955493.4515   13960802.0783    2955499.6069     13960425.52
    2955535.3355   13959646.2199    2955572.0043   13958634.9312
    2955640.0122    13956865.101
#Sta/Elev= 30
    3256  249.78  3326.7  249.98  4115.5  244.88  4185.5  245.28  4605.6  241.88
  4675.6  243.08  4755.6  241.78  4882.5  242.88  4936.6  242.16  4944.5  242.06
  4971.7   236.1  4977.9  234.01  4989.3  233.95  4998.8  232.24  5008.8  233.67
  5011.6  232.62  5012.5  234.66  5031.3  237.92  5044.6  240.38  5091.8   241.6
  5450.3  241.69  5747.6  240.78  6007.6  242.88  6117.6  242.28  6317.6  244.88
  6527.6  244.98  6677.6  247.28  6707.6  246.48    6794  247.47  7195.9  249.98
#Mann= 7 ,-1 , 0
    3256      .2       0  3326.7     .08       0  4936.6     .15       0
  4971.7     .07       0  5031.3     .15       0  5450.3     .07       0
    6794      .2       0
#XS Ineff= 2 , 0
       0  4934.5  241.81  5054.5       0   241.7
Permanent Ineff=
       F       F
Bank Sta=4971.7,5031.3
XS Rating Curve= 0
Exp/Cntr=.5,.3

Type RM Length L Ch R = 3 ,15696.4 ,,,
BEGIN DESCRIPTION:
KICKAPOO
Structure ID: J158-00-00-01
END DESCRIPTION:
Bridge Culvert--1,0,-1,-1, 0
Deck Dist Width WeirC Skew NumUp NumDn MinLoCord MaxHiCord MaxSubmerge Is_Ogee
10,45,2.6,0, 60, 60, , , .95, 0, 1,1,,
    3256  3326.7    3396  3476.7  3586.7  3675.5  3774.1  3815.5  3835.5  3855.5
  4085.5  4115.5  4155.5  4165.5  4185.5  4205.5  4335.5  4585.6  4605.6  4635.6
  4685.6  4705.6  4735.6  4755.6  4816.1  4828.3  4882.5 4932.21  4932.3 4942.59
  4942.7  5046.9 5047.01 5047.09  5047.2  5091.8  5144.3  5199.2  5266.1  5450.3
  5627.6  5747.6  5808.5  6007.6  6117.6  6207.6  6297.6  6317.6  6527.6  6617.6
  6628.5  6677.6  6707.6  6747.6  6887.6  6927.6  6977.6  7077.6  7147.6  7195.9
   249.8  250.01   249.7  248.41  249.01  247.81   247.7  246.61  247.31  246.61
  245.91  245.14  244.81  245.41  245.31  244.61  244.31  242.51  242.31   242.1
  243.11  242.41  242.61  241.81  242.64  244.75  244.85  244.84  244.84  244.84
  247.24  247.24  244.84  244.84  244.84  244.95  244.79   244.2   241.8  241.72
  242.06  242.69   242.2  243.03  243.79  244.02  244.31  244.91  246.53  246.71
   246.1  247.31  246.84  247.51  248.33  248.41  248.11  249.41  249.77     250
   249.8     250  249.26   248.4     249   247.8  247.49   246.6   247.3   246.6
   245.9   244.9   244.8   245.4   245.3   244.6   244.3   242.5   241.9   241.8
   243.1   242.4   242.6   241.8  242.63  242.67   242.9  242.24  243.34  243.34
  243.34  243.34  243.34  243.34  240.48  241.62  241.93  241.22  241.74  241.71
   241.8   240.8  241.05   242.9   242.3   242.9   244.3   244.9     245   246.7
   246.1   247.3   246.5   247.5   247.5   248.4   248.1   249.4   249.3     250
    3256  3326.7    3396  3476.7  3586.7  3675.5  3774.1  3815.5  3835.5  3855.5
  4085.5  4115.5  4155.5  4165.5  4185.5  4205.5  4335.5  4585.6  4605.6  4635.6
  4685.6  4705.6  4735.6  4755.6  4816.1  4828.3  4882.5 4932.21  4932.3 4942.59
  4942.7  5046.9 5047.01 5047.09  5047.2  5091.8  5144.3  5199.2  5266.1  5450.3
  5627.6  5747.6  5808.5  6007.6  6117.6  6207.6  6297.6  6317.6  6527.6  6617.6
  6628.5  6677.6  6707.6  6747.6  6887.6  6927.6  6977.6  7077.6  7147.6  7195.9
   249.8  250.01   249.7  248.41  249.01  247.81   247.7  246.61  247.31  246.61
  245.91  245.14  244.81  245.41  245.31  244.61  244.31  242.51  242.31   242.1
  243.11  242.41  242.61  241.81  242.64  244.75  244.85  244.84  244.84  244.84
  247.24  247.24  244.84  244.84  244.84  244.95  244.79   244.2   241.8  241.72
  242.06  242.69   242.2  243.03  243.79  244.02  244.31  244.91  246.53  246.71
   246.1  247.31  246.84  247.51  248.33  248.41  248.11  249.41  249.77     250
  249.67  249.87  249.13  248.27  248.87  247.67  247.36  246.47  247.17  246.47
  245.77  244.77  244.67  245.27  245.17  244.47  244.17  242.37  241.77  241.67
  242.97  242.27  242.47  241.67   242.5  242.54  242.77  242.11  243.21  243.21
  243.21  243.21  243.21  243.21  240.35  241.49   241.8  241.09  241.61  241.58
  241.67  240.67  240.92  242.77  242.17  242.77  244.17  244.77  244.87  246.57
  245.97  247.17  246.37  247.37  247.37  248.27  247.97  249.27  249.17  249.87
Pier Skew, UpSta & Num, DnSta & Num=  ,4977.9, 2 ,4977.9, 2 , 0 , 0 , 0 ,,
     1.5     1.5
  233.03  244.33
     1.5     1.5
   232.9   244.2
Pier Skew, UpSta & Num, DnSta & Num=  ,5012.5, 2 ,5012.5, 2 , 0 , 0 , 0 ,,
     1.5     1.5
  231.98  244.32
     1.5     1.5
  231.85  244.19
Abutment Skew #Up #Dn= , 2 , 2
  4932.1  4944.6
  243.34  242.05
  4932.1  4944.6
  243.21  241.92
Abutment Skew #Up #Dn= , 2 , 2
  5044.6 5047.29
   240.4  243.34
  5044.6 5047.29
  240.27  243.21
BR Coef= 1 , 1 , 1 ,1.25, 0 ,,,.8,0,2,0,
WSPro=,,,, 1 ,,,, 0 ,,,, 0 ,,,,-1 ,-1 ,-1 , 0 , 0 , 0 , 0 , 0
BR U #Sta/Elev= 30
    3256   249.8  3326.7     250  4115.5   244.9  4185.5   245.3  4605.6   241.9
  4675.6   243.1  4755.6   241.8  4882.5   242.9  4936.6  242.18  4944.5  242.08
  4971.7  236.12  4977.9  234.03  4989.3  233.97  4998.8  232.26  5008.8  233.69
  5011.6  232.64  5012.5  234.68  5031.3  237.94  5044.6   240.4  5091.8  241.62
  5450.3  241.71  5747.6   240.8  6007.6   242.9  6117.6   242.3  6317.6   244.9
  6527.6     245  6677.6   247.3  6707.6   246.5    6794  247.49  7195.9     250
BR U #Mann= 7
    3256      .2  3326.7     .08  4936.6     .15  4971.7     .06  5031.3     .15
  5450.3     .07    6794      .2
BR U Banks=4971.7,5031.3
BR D #Sta/Elev= 30
    3256  249.67  3326.7  249.87  4115.5  244.77  4185.5  245.17  4605.6  241.77
  4675.6  242.97  4755.6  241.67  4882.5  242.77  4936.6  242.05  4944.5  241.95
  4971.7  235.99  4977.9   233.9  4989.3  233.84  4998.8  232.13  5008.8  233.56
  5011.6  232.51  5012.5  234.55  5031.3  237.81  5044.6  240.27  5091.8  241.49
  5450.3  241.58  5747.6  240.67  6007.6  242.77  6117.6  242.17  6317.6  244.77
  6527.6  244.87  6677.6  247.17  6707.6  246.37    6794  247.36  7195.9  249.87
BR D #Mann= 7
    3256      .2  3326.7     .08  4936.6     .15  4971.7     .06  5031.3     .15
  5450.3     .07    6794      .2
BR D Banks=4971.7,5031.3
BC Design=,, 0 ,, 0 ,,,,,,

Type RM Length L Ch R = 1 ,15663.9 ,137.6,137.6,137.6
BEGIN DESCRIPTION:
Downstream Section of Bridge/Culvert/Weir
END DESCRIPTION:
XS GIS Cut Line= 5
    2955537.1178   13960842.4346    2955545.3455   13960584.4439
    2955597.5132   13959583.8311    2955644.7665   13958532.4456
    2955704.5407   13956906.1515
#Sta/Elev= 30
    3256  249.65  3326.7  249.85  4115.5  244.75  4185.5  245.15  4605.6  241.75
  4675.6  242.95  4755.6  241.65  4882.5  242.75  4936.6  242.03  4944.5  241.93
  4971.7  235.97  4977.9  233.88  4989.3  233.82  4998.8  232.11  5008.8  233.54
  5011.6  232.49  5012.5  234.53  5031.3  237.79  5044.6  240.25  5091.8  241.47
  5450.3  241.56  5747.6  240.65  6007.6  242.75  6117.6  242.15  6317.6  244.75
  6527.6  244.85  6677.6  247.15  6707.6  246.35    6794  247.34  7195.9  249.85
#Mann= 7 ,-1 , 0
    3256      .2       0  3326.7     .08       0  4936.6     .15       0
  4971.7     .07       0  5031.3     .15       0  5450.3     .07       0
    6794      .2       0
#XS Ineff= 2 , 0
       0 4937.83  241.81 5051.17       0   241.7
Permanent Ineff=
       F       F
Bank Sta=4971.7,5031.3
XS Rating Curve= 0
Exp/Cntr=.5,.3

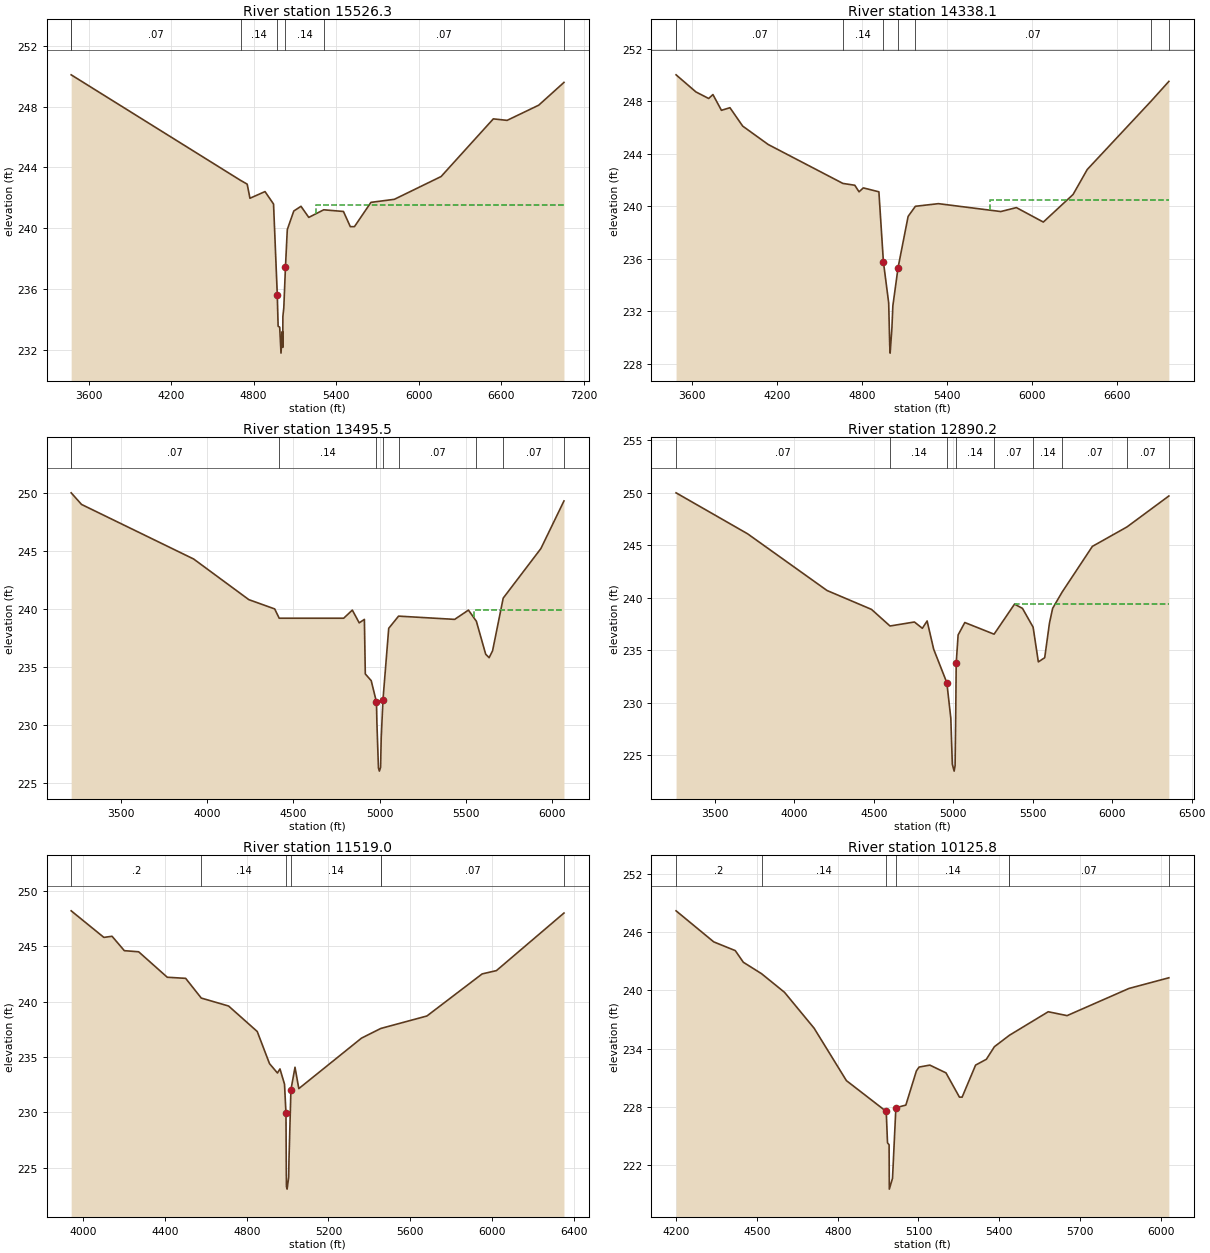
Type RM Length L Ch R = 1 ,15526.3 ,832.25,1188.2,816.07
BEGIN DESCRIPTION:
Cross Section XS12
END DESCRIPTION:
XS GIS Cut Line= 2
    2955658.8914   13960675.6267    2955829.3491   13957096.0163
#Sta/Elev= 30
  3472.9   250.1  4704.5  243.15  4752.9   242.9    4773  241.97  4882.5  242.41
  4944.6  241.59  4971.7  235.63  4977.9  233.54  4989.3  233.48  4998.8  231.77
  5008.8   233.2  5011.6  232.15  5012.5  234.19  5019.2  234.76  5031.3  237.45
  5044.6  239.91  5091.8  241.13  5144.3  241.44  5200.7  240.71  5309.5  241.21
  5452.9   241.1  5502.9   240.1  5532.9   240.1  5652.9   241.7  5822.9   241.9
  6162.9   243.4  6542.9   247.2  6642.9   247.1  6872.9   248.1  7056.6   249.6
#Mann= 7 , 1 , 0
  3472.9      .2       0  3472.9     .07       0  4704.5     .14       0
  4971.7     .07       0  5031.3     .14       0  5309.5     .07       0
  7056.6      .2       0
#XS Ineff= 2 , 0
       0                    5250       0   241.5
Permanent Ineff=
       F       F
Bank Sta=4971.7,5031.3
XS Rating Curve= 0
Exp/Cntr=.3,.1

Type RM Length L Ch R = 1 ,14338.1 ,587.02,842.6,467.07
BEGIN DESCRIPTION:
Cross Section XS11
END DESCRIPTION:
XS GIS Cut Line= 3
    2956313.2677   13960570.3772    2956359.1871   13959610.6089
    2956826.5263   13957138.6307
#Sta/Elev= 30
  3486.5     250  3626.5   248.7  3716.5   248.2  3746.5   248.5  3806.5   247.3
  3866.5   247.5  3956.5   246.1  4136.5   244.7  4663.3  241.74  4747.4   241.6
  4777.4   241.1  4807.4   241.4  4917.4   241.1  4949.2  235.78  4986.5  232.65
  4993.8  229.42  4996.8  228.83  5009.3  230.75  5015.8  232.42  5052.8  235.34
  5123.6  239.23  5174.9     240  5337.4   240.2  5777.4   239.6  5887.4   239.9
  6077.4   238.8  6287.4   240.9  6387.4   242.8  6837.9     248  6963.1   249.5
#Mann= 8 , 1 , 0
  3486.5      .2       0  3486.5     .07       0  4663.3     .14       0
  4949.2     .07       0  5052.8     .14       0  5174.9     .07       0
  6837.9     .07       0  6963.1      .2       0
#XS Ineff= 2 , 0
       0                    5700       0   240.5
Permanent Ineff=
       F       F
Bank Sta=4949.2,5052.8
XS Rating Curve= 0
Exp/Cntr=.3,.1

Type RM Length L Ch R = 1 ,13495.5 ,538.75,605.3,564.06
BEGIN DESCRIPTION:
Cross Section XS10
END DESCRIPTION:
XS GIS Cut Line= 3
    2956680.0941   13960517.8052    2956996.1766   13958549.7443
    2957258.5848    13957726.737
#Sta/Elev= 30
  3212.3     250  3272.3     249  3922.3   244.3  4242.3   240.8  4392.3     240
  4418.3   239.2  4792.3   239.2  4842.3   239.9  4882.3   238.8  4912.3   239.1
  4917.6   234.4  4951.9  233.82  4982.4  231.97  4984.8  230.21  4993.8   226.3
  4999.2  226.03  5006.2  226.36  5009.9  228.91  5020.1  232.19  5053.4  238.33
  5110.5  239.38  5435.6   239.1  5515.6   239.9  5561.5  238.94  5615.6   236.1
  5635.6   235.8  5655.6   236.4  5717.1  240.93  5935.6   245.2  6069.4   249.3
#Mann= 9 , 1 , 0
  3212.3      .2       0  3212.3     .07       0  4418.3     .14       0
  4982.4     .07       0  5020.1     .14       0  5110.5     .07       0
  5561.5     .14       0  5717.1     .07       0  6069.4      .2       0
#XS Ineff= 2 , 0
       0                    5545       0   239.9
Permanent Ineff=
       F       F
Bank Sta=4982.4,5020.1
XS Rating Curve= 0
Exp/Cntr=.3,.1

Type RM Length L Ch R = 1 ,12890.2 ,1149.57,1371.2,1237.85
BEGIN DESCRIPTION:
Cross Section XS09
END DESCRIPTION:
XS GIS Cut Line= 2
    2957079.6701   13960637.0816    2957795.3286   13957619.3883
#Sta/Elev= 30
  3255.1     250  3705.1   246.1  4205.1   240.7  4485.1   238.9  4601.5  237.32
  4755.1   237.7  4805.1   237.1  4835.1   237.8  4876.3  235.11  4959.2  231.92
  4984.3  228.53  4993.7  224.16  5005.2   223.5  5011.1  224.01  5015.7  229.71
  5018.1  233.77  5030.2  236.47  5072.3  237.65  5256.5  236.54  5385.1   239.4
  5435.1     239  5502.1  237.21  5535.1   233.9  5575.1   234.3  5605.1   237.6
  5625.1     239    5684  240.53  5875.1   244.9  6092.7  246.75  6356.5   249.7
#Mann= 9 ,-1 , 0
  3255.1     .07       0  4601.5     .14       0  4959.2     .07       0
  5018.1     .14       0  5256.5     .07       0  5502.1     .14       0
    5684     .07       0  6092.7     .07       0  6356.5      .2       0
#XS Ineff= 2 , 0
       0                    5390       0   239.4
Permanent Ineff=
       F       F
Bank Sta=4959.2,5018.1
XS Rating Curve= 0
Exp/Cntr=.3,.1

Type RM Length L Ch R = 1 ,11519.0 ,1268.85,1393.2,1222.98
BEGIN DESCRIPTION:
Cross Section XS08
END DESCRIPTION:
XS GIS Cut Line= 2
    2958332.2763   13960607.4232    2958711.9981   13958227.2158
#Sta/Elev= 30
  3941.5   248.2  4101.5   245.8  4141.5   245.9  4201.5   244.6  4271.5   244.5
  4411.5   242.2  4501.5   242.1  4577.8  240.32  4711.5   239.6  4851.5   237.3
  4911.5   234.4  4950.4  233.55  4962.7  233.92    4985  232.54  4992.1  229.91
  4993.7  224.76  4994.5   223.3  4997.6  223.06  5005.4  224.14  5006.6  225.56
  5016.3  232.03  5036.3  234.07  5054.9  232.14  5361.5   236.7  5456.7  237.58
  5457.1  237.58  5681.5   238.7  5951.5   242.5  6021.5   242.8  6351.8     248
#Mann= 7 , 1 , 0
  3941.5      .2       0  4577.8     .14       0  4992.1     .07       0
  5016.3     .14       0  5456.7     .07       0  5457.1     .07       0
  6351.8      .2       0
Bank Sta=4992.1,5016.3
XS Rating Curve= 0
Exp/Cntr=.3,.1

Type RM Length L Ch R = 1 ,10125.8 ,1235.03,1531.1,982.05
BEGIN DESCRIPTION:
Cross Section XS07
END DESCRIPTION:
XS GIS Cut Line= 3
    2959673.9322   13960303.1076    2959763.3895   13959951.2422
    2959703.7513   13958484.1423
#Sta/Elev= 30
  4199.1   248.2  4339.1     245  4419.1   244.1  4449.1   242.9  4516.8  241.72
  4602.2   239.8  4712.2   236.1  4832.2   230.7  4980.1  227.53  4984.9  224.29
  4990.8  224.09  4991.6  219.52  5003.5  220.64    5016  227.91    5053  228.18
  5092.2   231.7  5102.2   232.1  5142.2   232.3  5202.2   231.5  5252.2     229
  5262.2     229  5312.2   232.3  5352.2   232.9  5382.2   234.2  5437.3  235.36
  5437.6  235.37  5582.2   237.8  5652.2   237.4  5882.2   240.2  6030.5   241.3
#Mann= 7 , 1 , 0
  4199.1      .2       0  4516.8     .14       0  4980.1     .07       0
    5016     .14       0  5437.3     .07       0  5437.6     .07       0
  6030.5      .2       0
Bank Sta=4980.1,5016
XS Rating Curve= 0
Exp/Cntr=.3,.1

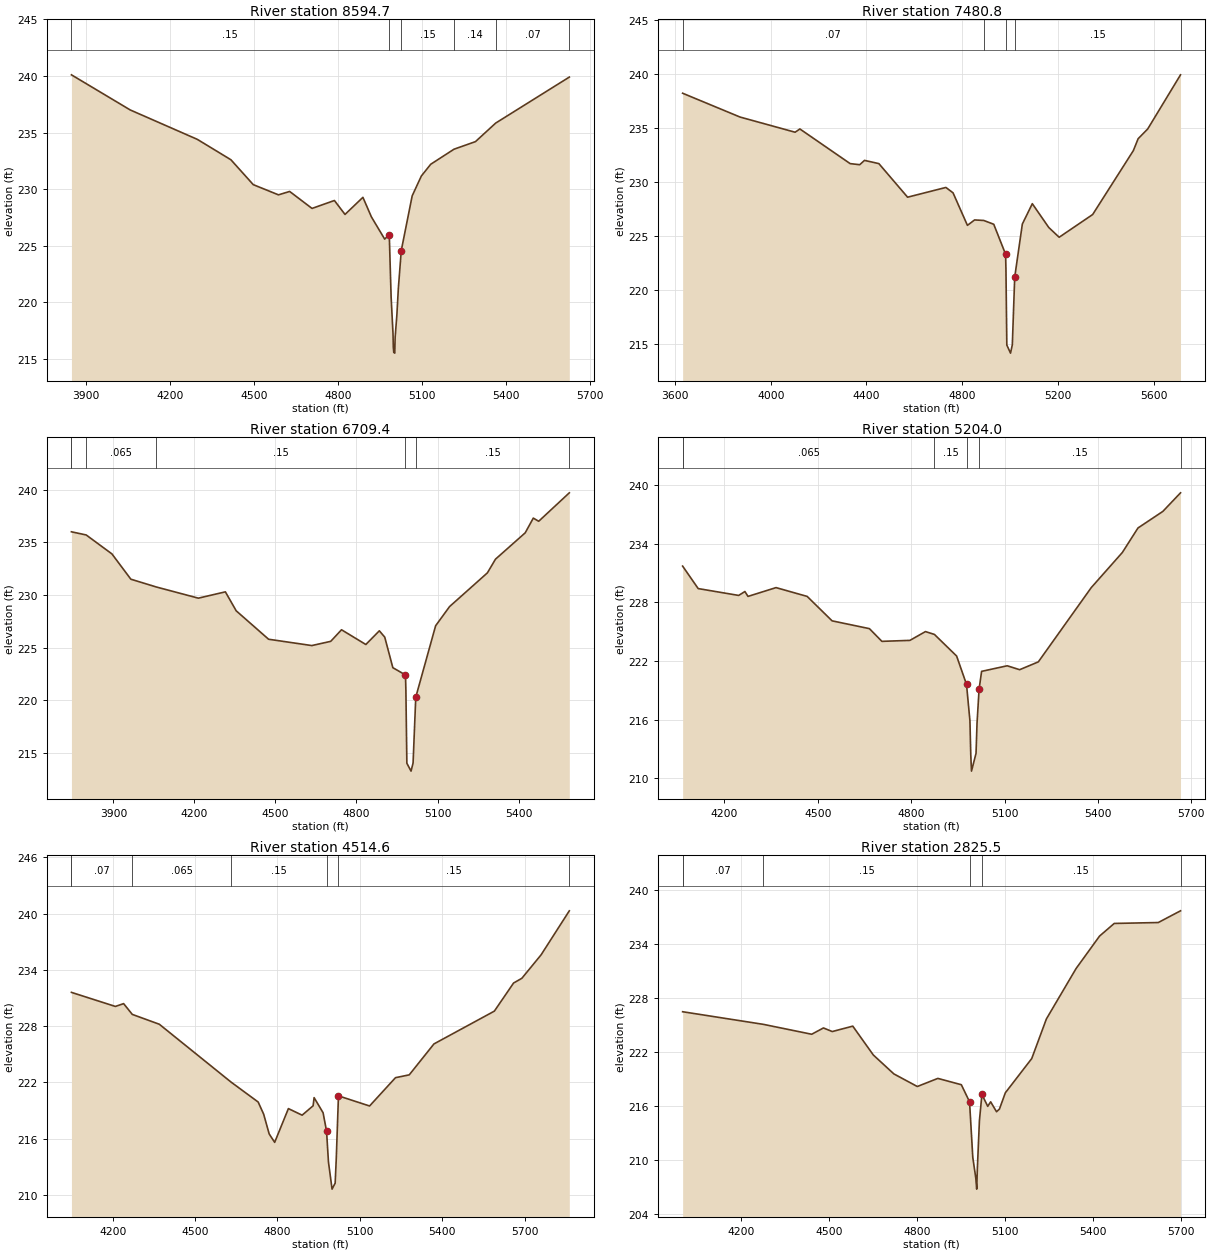
Type RM Length L Ch R = 1 ,8594.7  ,880.2,1113.9,1078.6
BEGIN DESCRIPTION:
Cross Section XS06
END DESCRIPTION:
XS GIS Cut Line= 3
    2960711.5452   13959901.8318    2960544.0915   13958911.6704
    2960223.7451   13958205.4524
#Sta/Elev= 30
  3846.7   240.1  4056.7     237  4296.7   234.4  4416.7   232.6  4496.7   230.4
  4586.7   229.5  4626.7   229.8  4706.7   228.3  4786.7     229  4824.6  227.77
  4888.6  229.28    4919  227.55  4966.4  225.59  4982.8  225.98  4989.4  220.49
  4996.2  217.22  4997.3  216.05  4998.8  215.59  5002.4  215.52  5003.8  216.92
    5010   218.9  5015.2  221.22  5025.7  224.58  5064.7  229.41  5097.4  231.16
  5130.9   232.2  5214.2  233.53  5290.9   234.2  5363.3  235.84  5626.4   239.9
#Mann= 6 ,-1 , 0
  3846.7     .15       0  4982.8     .07       0  5025.7     .15       0
  5214.2     .14       0  5363.3     .07       0  5626.4      .2       0
Bank Sta=4982.8,5025.7
XS Rating Curve= 0
Exp/Cntr=.3,.1

Type RM Length L Ch R = 1 ,7480.8  ,724.5,771.4,353.4
BEGIN DESCRIPTION:
Cross Section XS5.5
END DESCRIPTION:
XS GIS Cut Line= 3
    2961253.5849   13959906.1245    2961486.9633   13958350.2686
    2961236.2976   13957909.4428
#Sta/Elev= 30
  3631.9   238.2  3871.9     236  4101.9   234.6  4121.9   234.9  4331.9   231.7
  4371.9   231.6  4391.9     232  4451.9   231.7  4571.9   228.6  4731.9   229.5
  4761.9     229  4821.9     226  4851.9   226.5  4890.1  226.45  4931.9   226.1
  4981.4  223.33  4982.9  221.88  4986.5  214.95    5002   214.2  5009.5  214.97
  5019.5  221.22  5051.4  226.12    5093     228  5161.9   225.8  5205.2   224.9
  5345.2     227  5515.2   232.9  5535.2     234  5575.2   234.9  5712.3   239.9
#Mann= 5 ,-1 , 0
  3631.9     .07       0  4890.1     .15       0  4981.4     .07       0
  5019.5     .15       0  5712.3      .2       0
Bank Sta=4981.4,5019.5
XS Rating Curve= 0
Exp/Cntr=.3,.1

Type RM Length L Ch R = 1 ,6709.4  ,1083.23,1505.4,1332.59
BEGIN DESCRIPTION:
Cross Section XS05
END DESCRIPTION:
XS GIS Cut Line= 2
    2962417.2897    13959259.439    2961498.8613    13957661.135
#Sta/Elev= 30
  3744.6     236  3799.2   235.7  3894.6   233.9  3964.6   231.5    4059  230.76
  4214.6   229.7  4314.6   230.3  4354.6   228.5  4474.6   225.8  4634.6   225.2
  4704.6   225.6  4744.6   226.7  4834.6   225.3  4884.6   226.6  4904.6     226
  4934.6   223.1  4981.4  222.41  4982.9  220.96  4986.5  214.03    5002  213.28
  5009.5  214.05  5019.5   220.3    5093  227.08  5144.6   228.9  5284.6   232.1
  5314.6   233.4  5424.6   235.9  5454.6   237.3  5474.6     237    5588   239.7
#Mann= 7 , 1 , 0
  3744.6      .2       0  3744.6     .07       0  3799.2    .065       0
    4059     .15       0  4981.4     .07       0  5019.5     .15       0
    5588      .2       0
Bank Sta=4981.4,5019.5
XS Rating Curve= 0
Exp/Cntr=.3,.1

Type RM Length L Ch R = 1 ,5204.0  ,655.11,689.4,645.35
BEGIN DESCRIPTION:
Cross Section XS04
END DESCRIPTION:
XS GIS Cut Line= 3
    2962975.4666   13959051.3973    2962986.7784   13958038.9913
    2962811.4455   13957479.0573
#Sta/Elev= 30
  4065.8   231.7  4115.8   229.4  4245.8   228.7  4265.8   229.1  4275.8   228.6
  4365.8   229.5  4465.8   228.6  4545.8   226.1  4665.8   225.3  4705.8     224
  4795.8   224.1  4845.8     225  4874.5  224.71  4945.8   222.5  4977.6   219.6
  4988.6  215.87  4991.3  212.39  4993.6  210.72  5008.2  212.54  5011.4  215.62
    5018   219.1  5026.1  220.93  5108.3   221.5  5148.3   221.1  5208.3   221.9
  5378.3   229.5  5478.3   233.1  5528.3   235.6  5608.3   237.3    5665   239.2
#Mann= 6 , 1 , 0
  4065.8      .2       0  4065.8    .065       0  4874.5     .15       0
  4977.6     .07       0    5018     .15       0    5665      .2       0
Bank Sta=4977.6,5018
XS Rating Curve= 0
Exp/Cntr=.3,.1

Type RM Length L Ch R = 1 ,4514.6  ,1219.27,1689.1,837.99
BEGIN DESCRIPTION:
Cross Section XS03
END DESCRIPTION:
XS GIS Cut Line= 2
    2963747.2218   13958824.0801    2963454.9946   13957034.9338
#Sta/Elev= 30
  4049.9   231.6  4209.9   230.1  4239.9   230.4  4271.5  229.25  4369.9   228.2
  4631.1  222.03  4729.9   219.9  4749.9   218.6  4769.9   216.5  4789.9   215.6
  4839.9   219.2  4889.9   218.5  4929.9   219.5  4933.5  220.37  4966.2  218.76
  4978.8  216.81  4985.8   213.5  4998.9  210.61  5010.2  211.25  5014.2  213.86
  5022.2  220.56  5135.5  219.48  5229.9   222.5  5279.9   222.8  5369.9   226.1
  5589.9   229.6  5659.9   232.6  5689.9   233.1  5759.9   235.6  5862.8   240.3
#Mann= 7 , 1 , 0
  4049.9      .2       0  4049.9     .07       0  4271.5    .065       0
  4631.1     .15       0  4978.8     .07       0  5022.2     .15       0
  5862.8      .2       0
Bank Sta=4978.8,5022.2
XS Rating Curve= 0
Exp/Cntr=.3,.1

Type RM Length L Ch R = 1 ,2825.5  ,1408.36,1779.7,1516.09
BEGIN DESCRIPTION:
Cross Section XS02
END DESCRIPTION:
XS GIS Cut Line= 3
      2964824.24   13958369.0293    2964208.1379   13957177.5592
    2963912.8163   13956978.9808
#Sta/Elev= 30
  4000.3   226.5  4275.4   225.1  4440.3     224  4480.3   224.7  4510.3   224.3
  4580.3   224.9  4650.3   221.7  4720.3   219.6  4800.3   218.2  4870.3   219.1
  4950.3   218.4  4978.3  216.51  4989.4  210.33  4999.5  208.07  5002.8  206.81
  5004.9  209.04    5012  214.41  5020.5  217.32  5040.3     216  5050.3   216.5
  5070.3   215.4  5080.3   215.7  5100.3   217.5  5190.3   221.3  5240.3   225.7
  5341.6   231.3  5421.6   234.9  5471.6   236.3  5621.6   236.4  5697.5   237.7
#Mann= 6 , 1 , 0
  4000.3      .2       0  4000.3     .07       0  4275.4     .15       0
  4978.3     .07       0  5020.5     .15       0  5697.5      .2       0
Bank Sta=4978.3,5020.5
XS Rating Curve= 0
Exp/Cntr=.3,.1

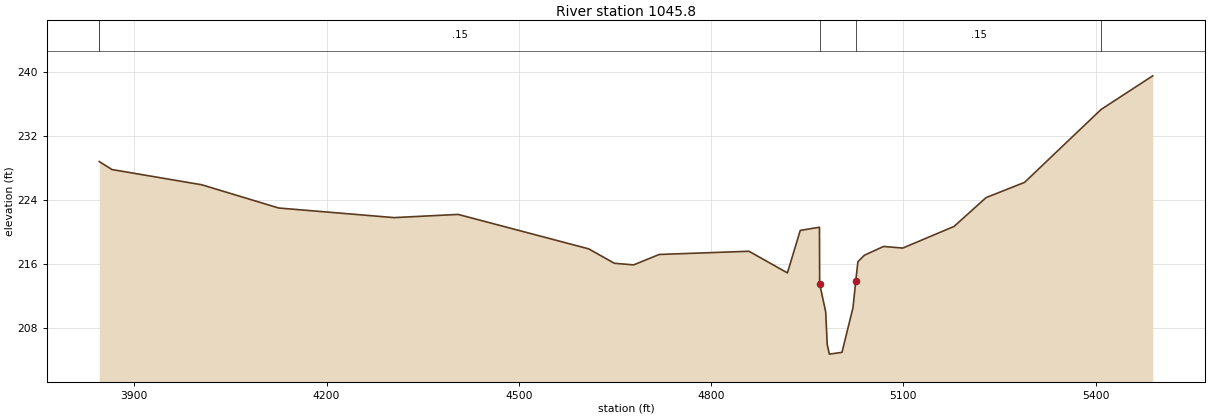
Type RM Length L Ch R = 1 ,1045.8  ,0,0,0
BEGIN DESCRIPTION:
Cross Section XS01
END DESCRIPTION:
XS GIS Cut Line= 3
    2965761.1225   13957982.0561     2965730.572   13957248.8437
    2965463.8339   13956378.8673
#Sta/Elev= 30
  3845.2   228.8  3865.2   227.8  4005.2   225.9  4125.2     223  4305.2   221.8
  4405.2   222.2    4609   217.9    4649   216.1    4679   215.9    4719   217.2
    4859   217.6    4919   214.9    4939   220.2    4969   220.6  4969.3  213.52
  4978.7  210.04  4981.1  205.96  4984.4  204.76  5004.1  204.98  5021.3  210.55
  5025.7  213.93    5029   216.3    5039   217.1    5069   218.2    5099     218
    5179   220.7    5229   224.3    5289   226.2  5408.4   235.3    5489   239.5
#Mann= 5 , 1 , 0
  3845.2      .2       0  3845.2     .15       0  4969.3     .07       0
  5025.7     .15       0  5408.4     .07       0
Bank Sta=4969.3,5025.7
XS Rating Curve= 0
Exp/Cntr=.3,.1

Chan Stop Cuts=-1